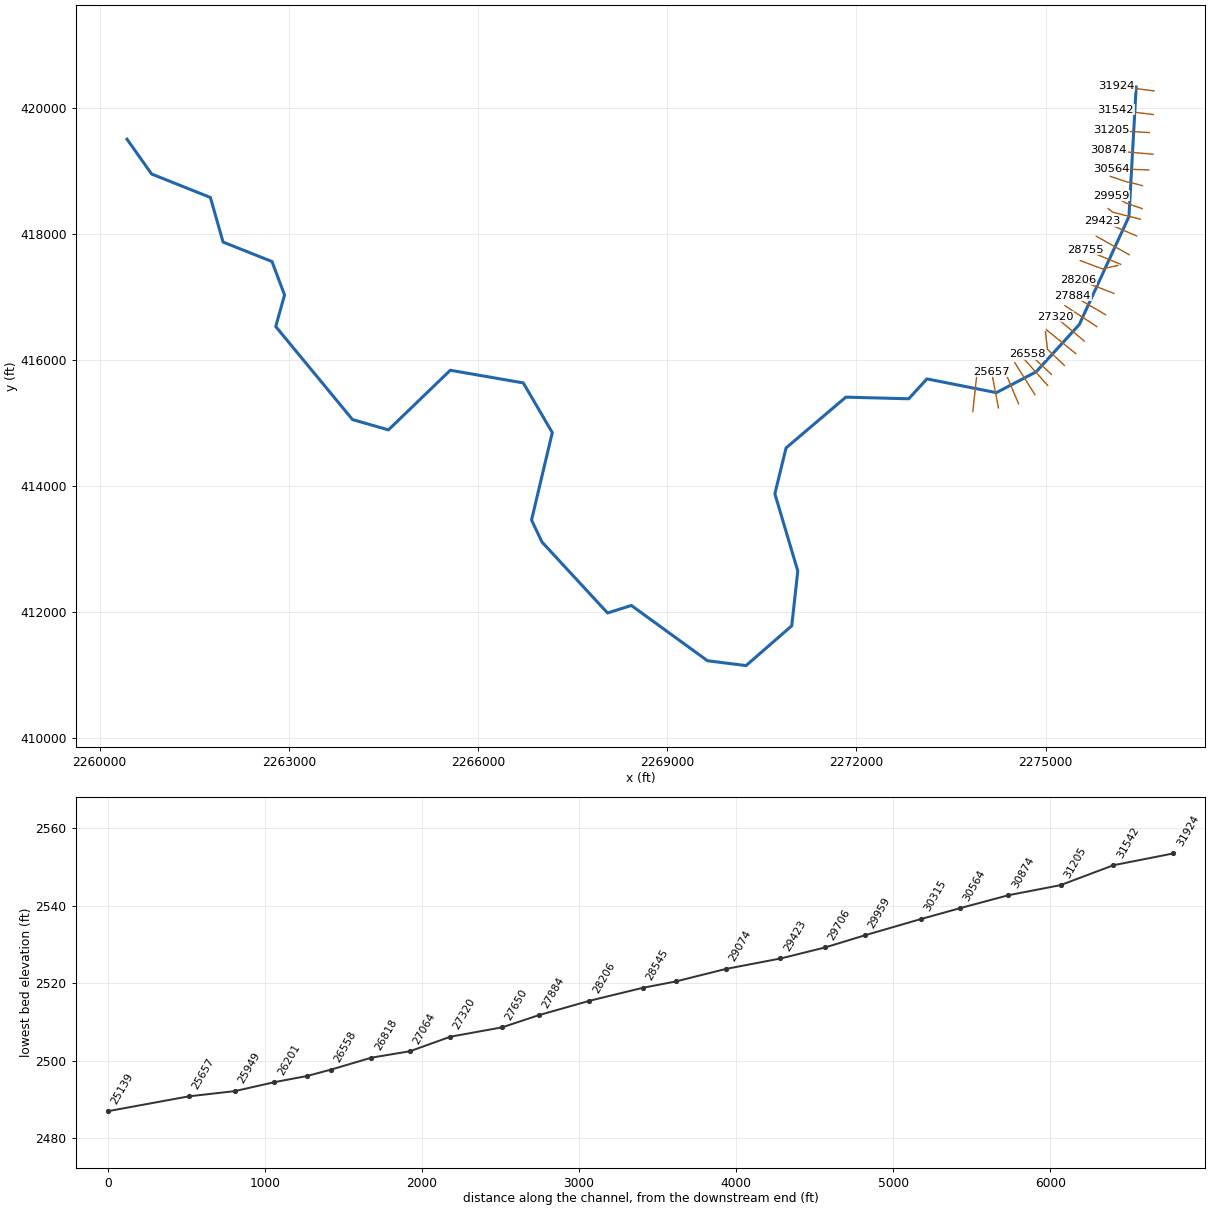
--- LAURELCK.prj (project) ---

Proj Title=LAURELCK
Current Plan=p01
Default Exp/Contr=0,0
English Units
Geom File=g01
Flow File=f01
Plan File=p01
Background Map Layer=Inundation Boundary (01pct Value_0)
BEGIN DESCRIPTION:
----------MODEL BY WOOD PLC 2021----------
Stream Name: Laurel Creek
Flood Zone: Enhanced Approximate
Pocahontas County, WV
HEC-RAS Version: RAS 6.1
Vertical Datum: NAVD88
Projection: NAD 1983 StatePlane West Virginia S FIPS 4702 (US Feet)
Terrain: 1-meter LIDAR (FEMA Region III 3DEP collected 2016-2018)
Land Use: 2019 NLCD
Hydrologic Method:
WV SIR2010-5033 regression equations
Model Notes:
Normal depth tie in to Douthat Creek
END DESCRIPTION:
DSS Export Rating Curves= 0
DSS Export Rating Curve Sorted= 0
DSS Export Volume Flow Curves= 0
DXF OffsetX= 0
DXF OffsetY= 0
DXF ScaleX= 0
DXF ScaleY= 0

--- LAURELCK.p01 (plan) ---

Plan Title=Floodplain
Program Version=6.10
Short Identifier=Floodplain
Geom File=g01
Flow File=f01
Subcritical Flow
K Sum by GR= 0
Std Step Tol= 0.01
Critical Tol= 0.01
Num of Std Step Trials= 20
Max Error Tol= 0.3
Flow Tol Ratio= 0.001
Split Flow NTrial= 30
Split Flow Tol= 0.02
Split Flow Ratio= 0.02
Log Output Level= 0
Friction Slope Method= 1
Unsteady Friction Slope Method= 2
Unsteady Bridges Friction Slope Method= 1
Parabolic Critical Depth
Global Vel Dist= 0 , 0 , 0
Global Log Level= 0
CheckData=True
Encroach Param=-1 ,0,0, 0
Mapping Interval=1HOUR
Computation Time Step Use Courant=        0
Computation Time Step Use Time Series=    0
Computation Time Step Count To Double=0
Computation Time Step Max Doubling=0
Computation Time Step Max Halving=0
Computation Time Step Residence Courant=0
Run HTab= 0
Run UNet= 0
Run Sediment= 0
Run PostProcess= 0
Run WQNet= 0
Run RASMapper=-1
UNET Theta= 0
UNET Theta Warmup= 0
UNET ZTol= 0
UNET ZSATol= 0
UNET MxIter= 0
UNET Max Iter WO Improvement= 0
UNET MaxInSteps= 0
UNET DtIC= 0
UNET DtMin= 0
UNET MaxCRTS= 0
UNET WFStab= 0
UNET SFStab= 0
UNET WFX= 1
UNET SFX= 1
UNET Gravity=32.174
UNET 1D Methodology=Finite Difference
UNET DSS MLevel= 1
UNET Pardiso=0
UNET DZMax Abort= 0
UNET Use Existing IB Tables= 0
UNET Froude Reduction=False
UNET Froude Limit= 0
UNET Froude Power= 0
UNET D1 Cores= 0
UNET WindReference=Eulerian
UNET WindDragFormulation=Hsu (1988)
UNET D2 Coriolis=0
UNET D2 Cores= 0
UNET D2 Theta= 1
UNET D2 Theta Warmup= 1
UNET D2 Z Tol= 0.01
UNET D2 Volume Tol= 0.01
UNET D2 Max Iterations= 20
UNET D2 Equation= 0
UNET D2 RampUpFraction=0.1
UNET D2 TimeSlices= 1
UNET D2 Turbulence Formulation=Non-Conservative (original)
UNET D2 Eddy Viscosity=0.3
UNET D2 Transverse Eddy Viscosity=0.1
UNET D2 Smagorinsky Mixing=0
UNET D2 BCVolumeCheck=0
UNET D2 Cores=0
UNET D2 SolverType=PARDISO (Direct)
UNET D2 Minimum Iterations= 2147483647
UNET D2 Maximum Iterations= 2147483647
UNET D2 Restart Number= 10
UNET D2 Relaxation Coeff=1.3
UNET D2 SOR Precondition Iterations= 10
UNET D2 ILUT Maximum Fill= 8
UNET D2 ILUT Tolerance=1E-08
UNET D1D2 MaxIter= 0
UNET D1D2 ZTol=0.01
UNET D1D2 QTol=0.1
UNET D1D2 MinQTol=1
Write IC File= 0
Write IC File at Fixed DateTime=0
Write IC File at Sim End=0
Echo Input=False
Echo Parameters=False
Echo Output=False
Write Detailed= 0
HDF Write Warmup=0
HDF Write Time Slices=0
HDF Flush=0
HDF Compression= 1
HDF Chunk Size= 1
HDF Spatial Parts= 1
HDF Use Max Rows=0
HDF Fixed Rows= 1
Calibration Method= 0
Calibration Iterations= 20
Calibration Max Change=0.05
Calibration Tolerance=0.2
Calibration Maximum=1.5
Calibration Minimum=0.5
Calibration Optimization Method= 1
WQ AD Non Conservative
WQ ULTIMATE=-1
WQ Max Comp Step=1HOUR
WQ Output Interval=15MIN
WQ Output Selected Increments= 0
WQ Output face flow=0
WQ Output face velocity=0
WQ Output face area=0
WQ Output face dispersion=0
WQ Output cell volume=0
WQ Output cell surface area=0
WQ Output cell continuity=0
WQ Output cumulative cell continuity=0
WQ Output face conc=0
WQ Output face dconc_dx=0
WQ Output face courant=0
WQ Output face peclet=0
WQ Output face adv mass=0
WQ Output face disp mass=0
WQ Output cell mass=0
WQ Output cell source sink temp=0
WQ Output nsm pathways=0
WQ Output nsm derived pathways=0
WQ Create Restart=0
WQ Fixed Restart=0
WQ System Summary=0
WQ Write To DSS=0
Sorting and Armoring Iterations= 10
XS Update Threshold= 0.02
Bed Roughness Predictor= 0
Hydraulics Update Threshold= 0.02
Energy Slope Method= 1
Volume Change Method= 1
Sediment Retention Method= 0
Sediment TS Multiplier= 1
Warm Up Method= 0
XS Weighting Method= 0
Number of US Weighted Cross Sections= 1
Number of DS Weighted Cross Sections= 1
Upstream XS Weight=0
Main XS Weight=1
Downstream XS Weight=0
Number of DS XS's Weighted with US Boundary= 1
Upstream Boundary Weight= 1
Weight of XSs Associated with US Boundary= 0
Number of US XS's Weighted with DS Boundary= 1
Downstream Boundary Weight= 0.5
Weight of XSs Associated with DS Boundary= 0.5
Percentile Method= 0
Sediment Output Level= 3
Mass or Volume Output= 0
Output Increment Type= 1
Profile and TS Output Increment= 1
Transport Output Increment 1
XS Output Flag= 0
XS Output Increment= 10
Read HDF5 Sediment Hotstart= 0
Sediment Hotstart Type= 0
Write Gradation File= 0
Read Gradation Hotstart= 0
Write HDF5 File= 1
Write Binary Output= 1
Write DSS Sediment File= 0
DSS Sediment Output Type= 1
SV Curve= 0
Specific Gage Flag= 0
Subcell Erosion Methods= 0
Subcell Deposition Methods= 0
Advection Scheme= 1
Matrix Solver= 0
Implicit Weighting Factor= 1
Maximum Outer Loop Convergence Iterations= 5
Convergence Maximum Absolute= 0.001
Convergence RMSE= 0.0001
Grain Fractions Max Abs Error= 0.001
Max Subgrid Regions= 1
Max Subgrid Length Scale= 3.402823E+38
Initial Layer Thickness= 3.402823E+38
Min Layer Thickness= 3.402823E+38
Max Layer Thickness= 3.402823E+38
Number of Layers= 5

--- LAURELCK.f01 (steady flow) ---

Flow Title=Flow
Program Version=6.10
Number of Profiles= 6
Profile Names=01pct,10pct,04pct,02pct,0_2pct,01plus
River Rch & RM=LAURELCK,Main            ,31924
     574     303     403     486     802     849
River Rch & RM=LAURELCK,Main            ,29423
     638     339     449     541     889     944
River Rch & RM=LAURELCK,Main            ,27064
     751     401     530     637    1040    1110
River Rch & RM=LAURELCK,Main            ,22638
     866     465     614     736    1200    1280
River Rch & RM=LAURELCK,Main            ,19853
     971     524     690     826    1340    1440
River Rch & RM=LAURELCK,Main            ,14670
    2450    1370    1770    2100    3330    3620
River Rch & RM=LAURELCK,Main            ,14214
    2730    1530    1980    2340    3700    4030
River Rch & RM=LAURELCK,Main            ,0
    4540    2600    3320    3910    6090    6710
Boundary for River Rch & Prof#=LAURELCK,Main            , 1
Up Type= 0
Dn Type= 1
Dn Known WS=2339.5
Boundary for River Rch & Prof#=LAURELCK,Main            , 2
Up Type= 0
Dn Type= 1
Dn Known WS=2338.4
Boundary for River Rch & Prof#=LAURELCK,Main            , 3
Up Type= 0
Dn Type= 1
Dn Known WS=2338.9
Boundary for River Rch & Prof#=LAURELCK,Main            , 4
Up Type= 0
Dn Type= 1
Dn Known WS=2339.3
Boundary for River Rch & Prof#=LAURELCK,Main            , 5
Up Type= 0
Dn Type= 1
Dn Known WS=2339.9
Boundary for River Rch & Prof#=LAURELCK,Main            , 6
Up Type= 0
Dn Type= 1
Dn Known WS=2340.1
DSS Import GetInterval= 0
DSS Import GetPeak= 0
DSS Import FillOption= 0

--- LAURELCK.g01 (geometry) ---

Geom Title=Geometry
Program Version=6.10

River Reach=LAURELCK        ,Main
Reach XY= 30
2276435.56514956420333.8831478952276321.08900055418277.945986807
2275533.12207255416564.8880612252274849.80257306 415815.45648922
2274218.88749631415484.6448148942273117.56784855415703.124036729
2272829.70490722415387.3539989742271832.63012972 415413.63413015
2270884.98110639414608.3109376432270707.05593731 413881.20215565
2271070.42299272412655.6800003952270974.65087456411785.786070898
2270250.24713963411154.4671235532269639.40092039411231.258964732
 2268431.3971028412108.6000578112268054.70002155411989.213157475
2267014.39796831413115.1249476372266849.10302331413463.533043474
2267178.01115814414851.0958851432266717.96089713 415639.61202465
 2265560.8989068415840.0181198872264580.39004105414894.268042892
2264010.79111464415057.2700134812262793.28009821416534.017059982
2262933.21092072417034.6108750552262734.04990172 417564.88212423
2261958.08491822417873.8329498922261757.67783873418581.293149143
2260825.36605506418953.5489663032260435.49019438419505.767021984

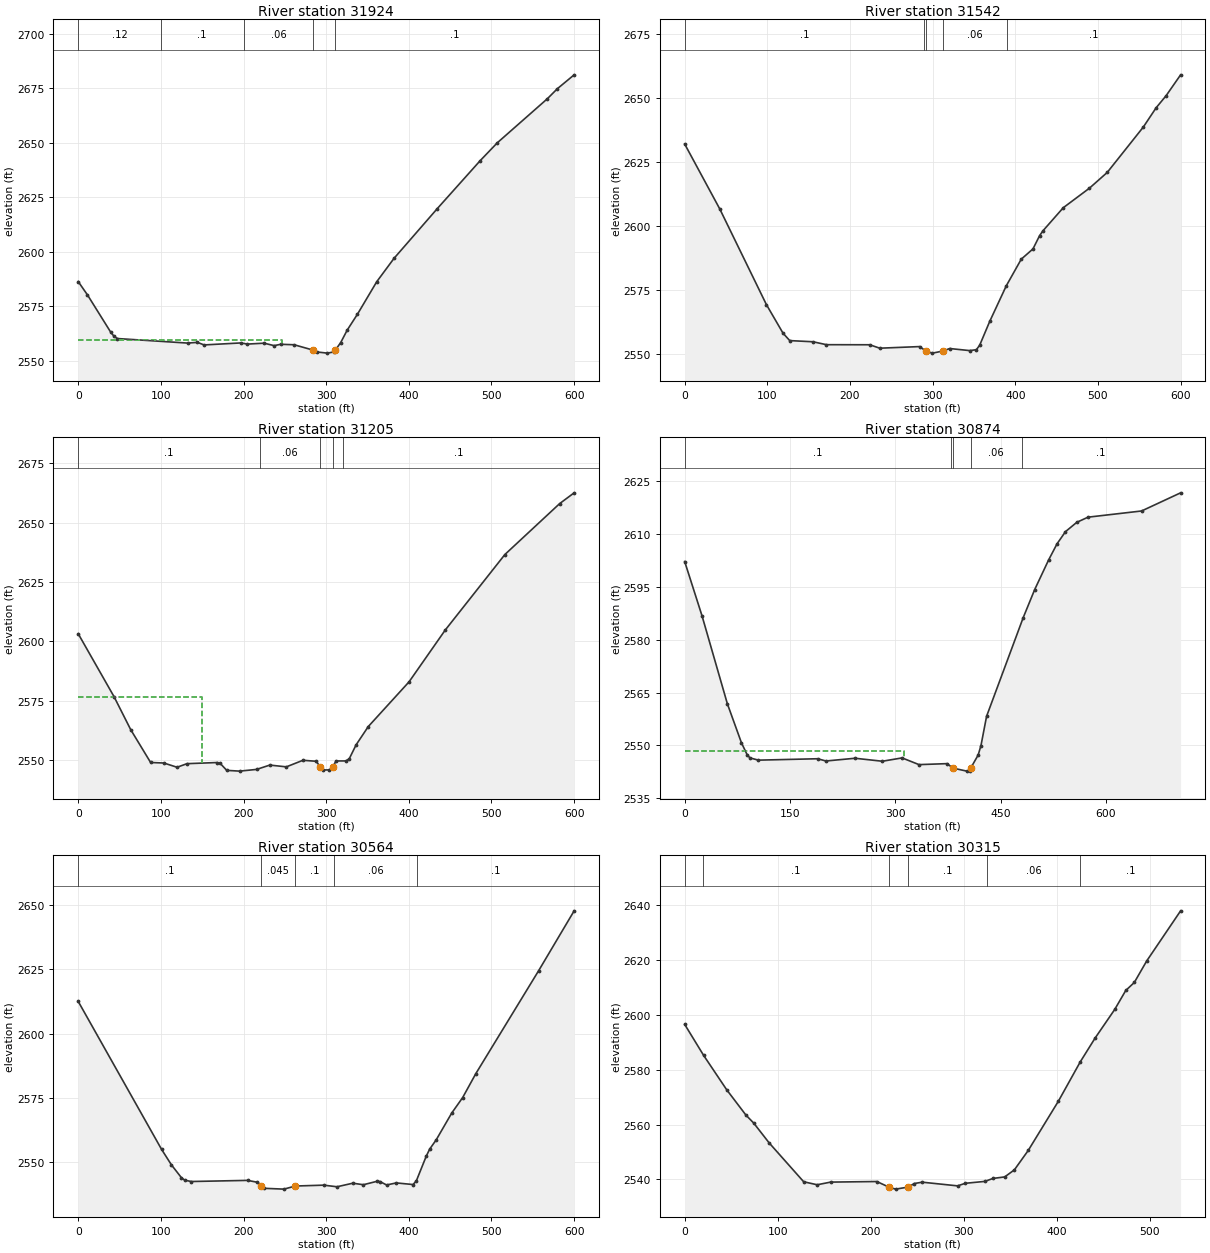
Type RM Length L Ch R = 1 ,31924   ,381.9,381.9,381.9
XS GIS Cut Line= 2
2276719.24530701420272.3401006082276124.03999423420348.041062563
#Sta/Elev= 30
       0 2586.27    11.2 2580.15    39.4 2563.02    43.4 2561.14    47.4 2560.14
   132.3 2558.06   144.2 2558.38   152.3 2557.21   196.6 2558.12   204.7  2557.6
   224.9 2558.01     237 2556.89     245  2557.5   261.2 2557.29   284.4 2554.81
   289.4 2553.95   301.5 2553.45   309.5 2554.02   311.1 2554.84   317.6 2558.31
   325.4 2563.99   337.8 2571.28   361.2 2586.22   382.1 2596.93   434.5 2619.77
   486.4 2641.76   507.1 2649.94   567.6 2670.13   579.7 2674.73     600 2681.09
#Mann= 5 ,-1,0
       0     .12       0     100      .1       0     200     .06       0
   284.4    .045       0   311.1      .1       0
#XS Ineff= 2 , 0
          247.05  2559.6
Permanent Ineff=
       F       F
Bank Sta=284.4,311.1
XS Rating Curve= 0 ,0
Exp/Cntr(USF)=0,0
Exp/Cntr=0.3,0.1

Type RM Length L Ch R = 1 ,31542   ,334.8,337,335.9
XS GIS Cut Line= 2
2276706.30064964419896.6364081822276110.94482447 419971.14440393
#Sta/Elev= 30
       0 2632.17    42.5 2606.75    98.9 2569.36     119 2558.19   127.1  2555.3
   155.3 2554.84   171.5  2553.7   223.9 2553.67     236 2552.33   284.3 2552.96
   292.1 2551.13   299.8  2550.4   312.5 2551.22   320.6  2552.2   344.8 2551.39
   352.9 2551.74   356.9 2553.49     369 2562.77   389.1 2576.73   407.2 2587.14
   421.4 2591.16   429.4 2596.34   433.5 2598.25     458 2607.25   489.7  2614.9
   511.2 2621.05   554.8 2638.77   570.5 2646.39   582.4 2651.04     600 2659.22
#Mann= 5 ,-1,0
       0      .1       0     290     .06       0   292.1    .045       0
   312.5     .06       0     390      .1       0
Bank Sta=292.1,312.5
XS Rating Curve= 0 ,0
Exp/Cntr(USF)=0,0
Exp/Cntr=0.3,0.1

Type RM Length L Ch R = 1 ,31205   ,330.8,331.6,330.8
XS GIS Cut Line= 2
2276643.62027198419611.0044092052276044.52376933419643.919155348
#Sta/Elev= 30
       0 2603.16    43.3 2576.67    63.5 2562.75    87.6  2548.9   103.6 2548.68
   119.6 2546.89   131.6  2548.4   167.7 2548.88   171.7 2548.55   179.7 2545.58
   195.2 2545.26   215.8 2545.98   231.8 2547.81   251.8 2547.06   271.9 2549.83
   287.9 2549.41  293.03 2546.97   295.9 2545.75   303.9 2545.77   307.9 2546.99
   311.9 2549.54   323.9 2549.56   327.9 2550.47   336.2 2556.34   350.9 2564.03
   400.3 2582.91   444.1 2604.75   516.2 2636.55   582.5 2658.02     600 2662.55
#Mann= 5 ,-1,0
       0      .1       0     220     .06       0  293.03    .045       0
   307.9     .06       0     320      .1       0
#XS Ineff= 2 , 0
           149.5 2576.54
Permanent Ineff=
       F       F
Bank Sta=293.03,307.9
XS Rating Curve= 0 ,0
Exp/Cntr(USF)=0,0
Exp/Cntr=0.3,0.1

Type RM Length L Ch R = 1 ,30874   ,307.1,309.7,310.7
XS GIS Cut Line= 2
2276704.76807293419267.4615066192276000.82209735419326.937636457
#Sta/Elev= 30
       0 2602.24    24.7 2586.81    60.8 2561.81    80.9  2550.7    88.9 2547.36
    92.9 2546.43     105 2545.78   189.3 2546.18   201.3 2545.54   242.7 2546.32
   281.6 2545.47   309.7 2546.42   333.8 2544.51   373.9 2544.79   381.9 2543.53
   401.9 2542.66     406 2542.72407.55652543.552   418.1 2547.24   422.1 2549.94
   430.1 2558.26   482.3 2586.31   498.6 2594.26   518.4 2602.67   530.5 2607.29
   542.5 2610.74   558.6 2613.39   574.6 2614.85   650.9 2616.61   706.5 2621.77
#Mann= 5 ,-1,0
       0      .1       0     380     .06       0   381.9    .045       0
407.5565     .06       0     480      .1       0
#XS Ineff= 2 , 0
          312.92 2548.47
Permanent Ineff=
       F       F
Bank Sta=381.9,407.5565
XS Rating Curve= 0 ,0
Exp/Cntr(USF)=0,0
Exp/Cntr=0.3,0.1

Type RM Length L Ch R = 1 ,30564   ,250.4,249.1,234.5
XS GIS Cut Line= 2
2276636.94815972 419017.846349482276037.34796595419039.746295301
#Sta/Elev= 30
       0 2612.52   100.8 2554.84   112.8 2548.75   124.9 2543.75   128.9 2542.78
   136.9 2542.27   204.9 2542.71   216.9 2541.97   221.7 2540.71   224.9 2539.62
   248.9  2539.3   262.7 2540.51     297 2540.85   313.1 2540.22   332.2 2541.61
     345 2541.02     361 2542.31     365 2542.27     373 2540.93     385 2541.72
     405 2541.09     409 2542.46   421.1 2552.18   425.2 2554.91   433.1 2558.52
   451.9 2568.98   465.1 2575.01   481.1 2584.39   557.1 2624.54     600 2647.86
#Mann= 5 ,-1,0
       0      .1       0   221.7    .045       0   262.7      .1       0
     310     .06       0     410      .1       0
Bank Sta=221.7,262.7
XS Rating Curve= 0 ,0
Exp/Cntr(USF)=0,0
Exp/Cntr=0.3,0.1

Type RM Length L Ch R = 1 ,30315   ,360.9,355.6,347.4
XS GIS Cut Line= 4
2276535.88877672418768.4981222862276329.22648217418823.537243757
2276297.83906169418824.1526833742276025.06387476418916.910308629
#Sta/Elev= 30
       0 2596.52    20.4 2585.21    45.2 2572.69    65.9 2563.46    74.2 2560.58
    90.8 2553.36     128 2539.17   142.5 2538.08     157 2539.05   206.7 2539.26
219.69452537.208   226.9 2536.49240.26232537.224     247 2538.54   255.5 2539.02
   293.5 2537.68   301.9 2538.62     323 2539.31   331.5 2540.38   344.2 2540.94
   354.6 2543.51   369.5 2550.58   401.9 2568.51   425.5 2582.88   441.4 2591.52
   462.5 2601.94   474.4 2608.87   483.6 2611.79   496.9 2619.61   533.4 2637.89
#Mann= 6 ,-1,0
       0     .06       0      20      .1       0219.6945    .045       0
240.2623      .1       0  325.26     .06       0  425.26      .1       0
Bank Sta=219.6945,240.2623
XS Rating Curve= 0 ,0
Exp/Cntr(USF)=0,0
Exp/Cntr=0.3,0.1

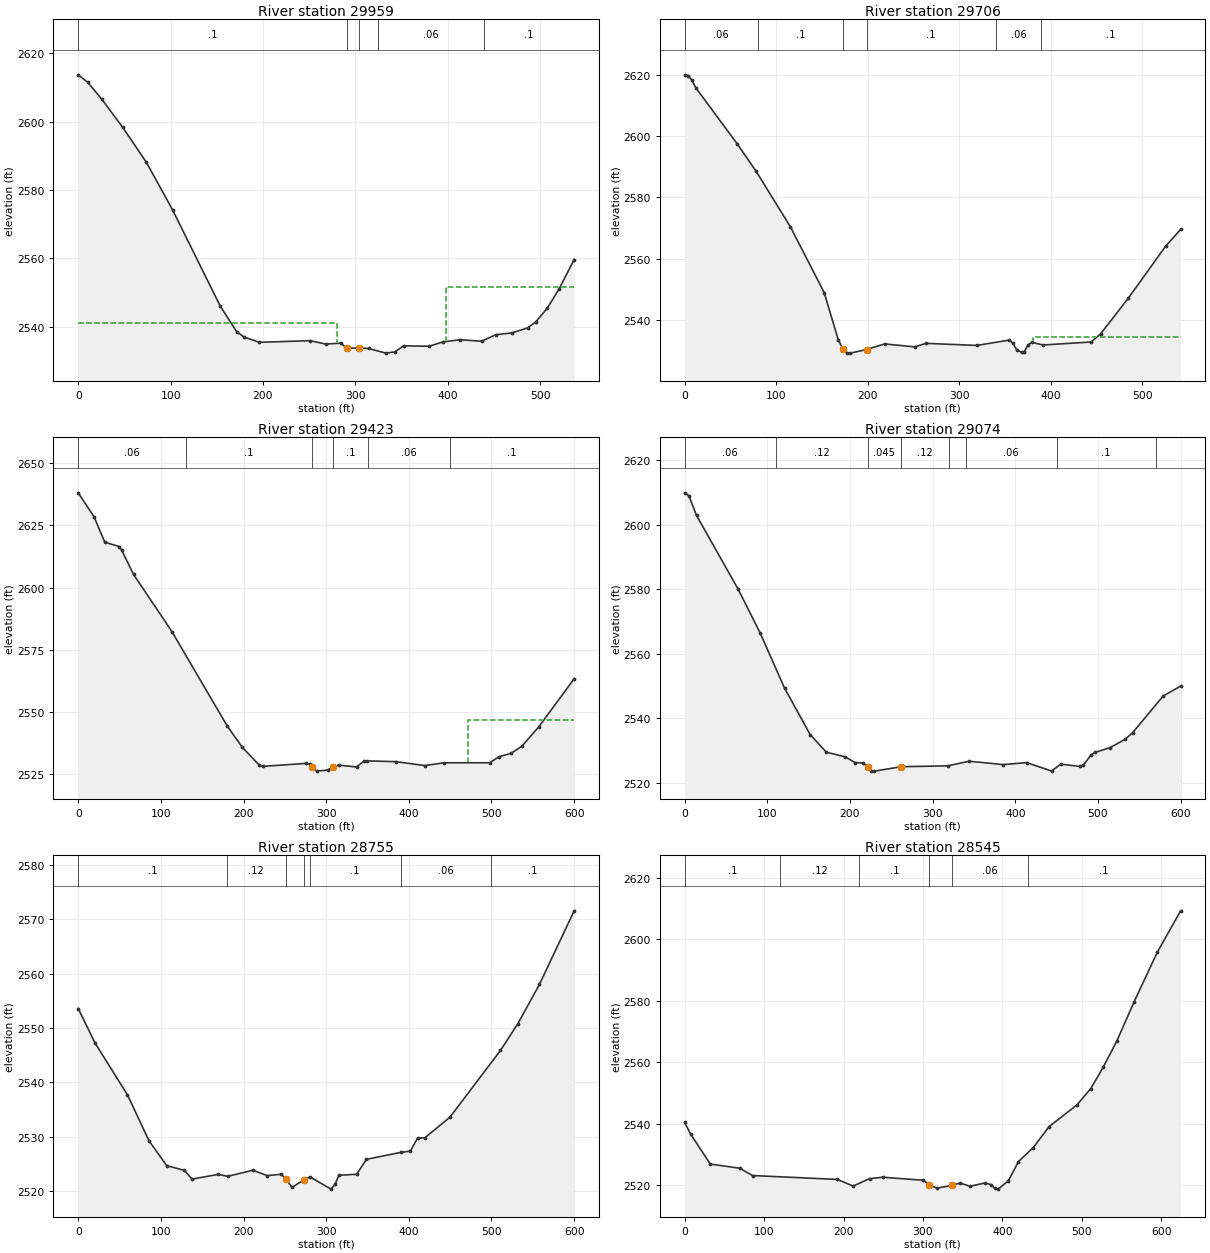
Type RM Length L Ch R = 1 ,29959   ,251.5,253,248.4
XS GIS Cut Line= 4
2276529.74659163418404.989529794  2276269.601804418493.860666726
2276156.29232806418565.375663841  2276037.247567418612.050336403
#Sta/Elev= 30
       0 2613.64    10.1 2611.51    25.3 2606.59    48.2 2598.28    73.9 2588.02
   102.2 2574.15   153.8 2546.01   171.5  2538.6   179.2 2537.05   196.1 2535.47
   251.1 2535.95     268 2534.96   284.1 2535.22   290.8 2533.77   303.6  2533.8
   314.4 2533.67     333 2532.31   342.8 2532.69   352.3 2534.45   379.8 2534.32
   394.3 2535.56   413.3 2536.24   436.6 2535.78     452 2537.69   469.2 2538.22
   486.4 2539.67   495.3 2541.45   507.6 2545.39   520.7 2551.18   536.8 2559.66
#Mann= 5 ,-1,0
       0      .1       0   290.8    .045       0   303.6      .1       0
  324.91     .06       0   438.9      .1       0
#XS Ineff= 2 , 0
             280 2541.16  397.67         2551.71
Permanent Ineff=
       F       F
Bank Sta=290.8,303.6
XS Rating Curve= 0 ,0
Exp/Cntr(USF)=0,0
Exp/Cntr=0.3,0.1

Type RM Length L Ch R = 1 ,29706   ,286.1,283.6,277.9
XS GIS Cut Line= 3
2276499.90862938418236.8434260672276063.41570843418348.044373908
2275991.68481909418405.091803023
#Sta/Elev= 30
       0  2619.9     3.9 2619.59       8  2618.1    12.1  2615.7    57.5 2597.36
    78.2 2588.39   115.5 2570.39   152.5 2548.92   167.8  2533.6172.90122530.553
   177.2 2529.21     181 2529.17198.7528 2530.33   218.5 2532.18   251.5 2531.21
   263.9 2532.36   319.2 2531.68   354.7 2533.41   358.6 2532.52     363  2530.2
   368.5 2529.43   371.2 2529.63   375.4 2531.91   379.5 2532.65   391.9 2531.83
   444.2  2532.8   454.6 2535.43   484.9 2547.09   526.1 2564.18   542.1 2569.48
#Mann= 6 ,-1,0
       0     .06       0      80      .1       0172.9012    .045       0
198.7528      .1       0     340     .06       0     390      .1       0
#XS Ineff= 2 , 0
                           380.8         2534.35
Permanent Ineff=
       F       F
Bank Sta=172.9012,198.7528
XS Rating Curve= 0 ,0
Exp/Cntr(USF)=0,0
Exp/Cntr=0.3,0.1

Type RM Length L Ch R = 1 ,29423   ,351,348.1,337.7
XS GIS Cut Line= 2
2276445.74429762 417969.859446372275894.14535504418205.949697216
#Sta/Elev= 30
       0 2638.11    19.1 2628.52    32.2 2618.25    49.6 2616.55    52.5 2615.14
      67 2605.31   113.4 2582.37   180.4 2544.38   198.7 2535.84   219.3 2528.67
   223.1 2528.23   275.8 2529.44   280.2 2529.06   282.9 2527.87   288.9 2526.33
   301.9 2526.79   308.4    2528     315 2528.74   336.7 2528.01   345.4  2530.3
   349.8 2530.45   384.6 2530.13   419.4 2528.55   442.5 2529.68   497.7 2529.68
   509.5 2532.15   523.8  2533.5   536.8 2536.36   557.4 2544.22     600 2563.44
#Mann= 6 ,-1,0
       0     .06       0     130      .1       0   282.9    .045       0
   308.4      .1       0     350     .06       0     450      .1       0
#XS Ineff= 2 , 0
                          471.43         2546.93
Permanent Ineff=
       F       F
Bank Sta=282.9,308.4
XS Rating Curve= 0 ,0
Exp/Cntr(USF)=0,0
Exp/Cntr=0.3,0.1

Type RM Length L Ch R = 1 ,29074   ,316.4,318.9,315.4
XS GIS Cut Line= 2
2276324.60903474417673.0478289722275801.71969413417967.304073565
#Sta/Elev= 30
       0 2609.83     5.1 2608.93    14.3 2602.84    64.8 2579.93    91.5 2566.31
   120.8 2549.35     152 2534.89   171.5 2529.48   194.3 2528.06     206 2526.29
   216.2 2526.16   221.2 2525.04   225.4 2523.75   229.5 2523.63   262.1    2525
   318.4 2525.27   344.1 2526.69   385.2 2525.66   413.6 2526.26   443.9 2523.67
   454.9 2525.79   477.8  2525.1   482.4 2525.49   491.6 2528.64   496.2 2529.41
   514.6  2530.9   532.9  2533.5   542.1 2535.58   578.8 2546.88     600 2549.97
#Mann= 8 ,-1,0
       0     .06       0     110     .12       0   221.2    .045       0
   262.1     .12       0     320      .1       0     340     .06       0
     450      .1       0     570     .12       0
Bank Sta=221.2,262.1
XS Rating Curve= 0 ,0
Exp/Cntr(USF)=0,0
Exp/Cntr=0.3,0.1

Type RM Length L Ch R = 1 ,28755   ,204.8,210.8,208.9
XS GIS Cut Line= 2
2276191.04095615 417519.889959912275637.38945072417751.125793063
#Sta/Elev= 30
       0 2553.57    20.4 2547.22    59.5 2537.74    85.7 2529.27   107.1 2524.72
   128.5 2523.84   137.7 2522.24   169.4 2523.11   180.8 2522.75   211.4 2523.87
   228.5 2522.89   245.9 2523.13   250.9 2522.23   258.9 2520.73   273.2 2522.14
   280.5 2522.63   305.9  2520.4   310.9 2521.31   315.2 2522.94   336.9 2523.13
   348.7 2525.87     390 2527.14   401.9 2527.39   410.6 2529.79   419.3 2529.83
   449.6 2533.59   510.8 2545.86     532 2550.81     558    2558     600 2571.51
#Mann= 7 ,-1,0
       0      .1       0     180     .12       0   250.9    .045       0
   273.2     .12       0     280      .1       0     390     .06       0
     500      .1       0
Bank Sta=250.9,273.2
XS Rating Curve= 0 ,0
Exp/Cntr(USF)=0,0
Exp/Cntr=0.3,0.1

Type RM Length L Ch R = 1 ,28545   ,334.1,338.7,334.4
XS GIS Cut Line= 3
2276143.74124745417502.4304759422275897.87738914 417448.28790879
2275549.20576537 417580.06903426
#Sta/Elev= 30
       0 2540.46     7.7 2536.58    32.3  2526.9    69.2 2525.56    85.6 2523.17
   192.1 2521.91   212.2 2519.76     233 2522.17   249.4 2522.62   300.6 2521.63
307.81092520.193   317.7 2519.07336.9098 2519.96   346.9 2520.74   359.3 2519.68
   377.9 2520.74   386.1 2520.23   390.4 2519.01   394.7 2518.75   407.5 2521.44
   420.3 2527.73   438.8 2532.23   458.8 2539.09   493.8 2546.13   511.3 2551.47
   526.9 2558.36   544.4 2567.09   565.7 2579.59   595.1 2595.84   624.5 2609.33
#Mann= 6 ,-1,0
       0      .1       0     120     .12       0     220      .1       0
307.8109    .045       0336.9098     .06       0  431.75      .1       0
Bank Sta=307.8109,336.9098
XS Rating Curve= 0 ,0
Exp/Cntr(USF)=0,0
Exp/Cntr=0.3,0.1

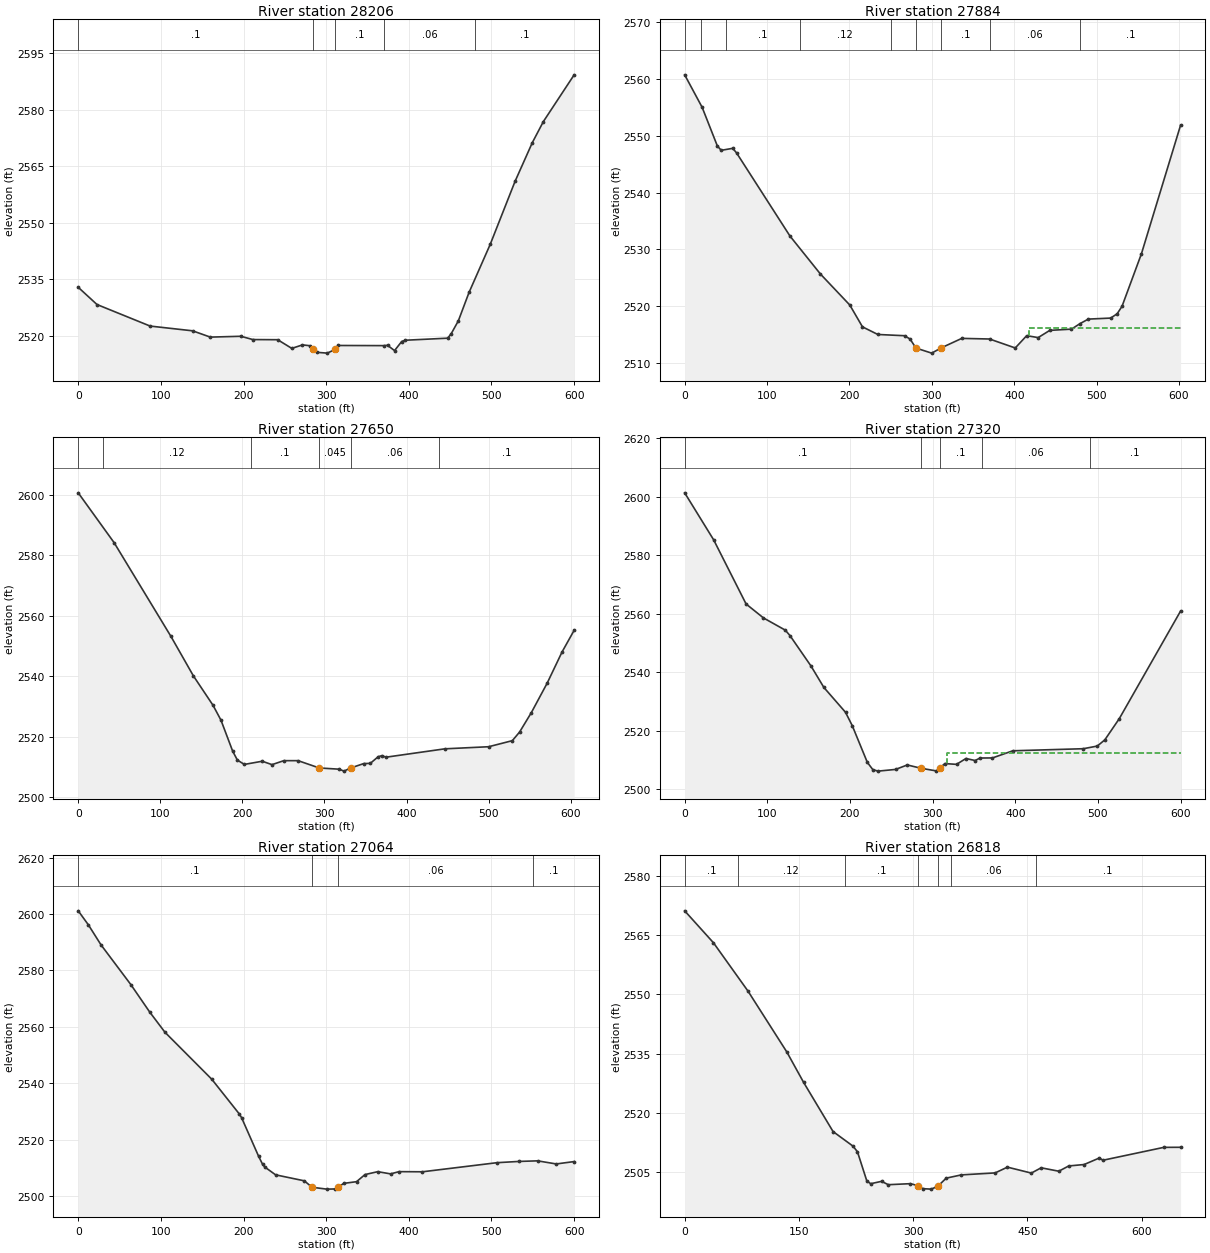
Type RM Length L Ch R = 1 ,28206   ,324.1,322.1,318.8
XS GIS Cut Line= 2
2276081.32114877 417060.068050522275521.45587367417275.824565456
#Sta/Elev= 30
       0 2532.88    22.7 2528.31      87 2522.59   138.4 2521.33   159.8 2519.66
   196.7 2519.88   211.3 2519.01   241.3 2518.97   258.4 2516.67   271.3 2517.59
   279.9 2517.39   284.2 2516.43   288.4 2515.63   301.3 2515.41   311.2 2516.42
   314.2 2517.44     370  2517.4   374.2 2517.49   382.7 2516.08   391.3 2518.48
   395.6 2518.83     447 2519.38   451.3 2520.58   459.9 2523.98   472.8  2531.5
   498.5  2544.3   528.5 2560.99   549.4 2571.27   562.8 2576.87     600 2589.26
#Mann= 5 ,-1,0
       0      .1       0   284.2    .045       0   311.2      .1       0
     370     .06       0     480      .1       0
Bank Sta=284.2,311.2
XS Rating Curve= 0 ,0
Exp/Cntr(USF)=0,0
Exp/Cntr=0.3,0.1

Type RM Length L Ch R = 1 ,27884   ,233.7,233.4,233.3
XS GIS Cut Line= 2
2275950.45853719416721.2931346212275430.94801539417025.228840689
#Sta/Elev= 30
       0 2560.77    21.2 2555.04    39.7 2548.21    44.4 2547.46    58.3 2547.81
    62.9 2547.02   127.8 2532.34   164.8 2525.64   200.4 2520.18   215.8 2516.33
   234.4 2514.99   266.8 2514.77   273.5 2514.19280.7482 2512.59   299.8  2511.7
311.54822512.639   336.3  2514.3     370 2514.19   401.2 2512.61   415.1 2514.78
     429 2514.44   443.1 2515.71   469.4 2515.93     480 2516.92   489.9  2517.7
     517 2517.88   524.9 2518.64   530.8 2519.96   554.3  2529.2   601.9 2551.91
#Mann= 9 ,-1,0
       0      .1       0      20     .12       0      50      .1       0
     140     .12       0     250      .1       0280.7482    .045       0
311.5482      .1       0     370     .06       0     480      .1       0
#XS Ineff= 2 , 0
                          417.65         2516.18
Permanent Ineff=
       F       F
Bank Sta=280.7482,311.5482
XS Rating Curve= 0 ,0
Exp/Cntr(USF)=0,0
Exp/Cntr=0.3,0.1

Type RM Length L Ch R = 1 ,27650   ,327.2,330.1,318.8
XS GIS Cut Line= 2
2275809.41274899416533.9222416262275304.64110748416866.067192647
#Sta/Elev= 30
       0 2600.62    43.7 2584.15     113 2553.11   140.3 2540.08   164.3 2530.31
   173.9 2525.43   188.2 2515.15   193.9 2512.22   202.4 2510.78   224.2 2511.83
   236.1 2510.71   250.5 2512.02   267.9 2512.02   293.6 2509.61     318  2509.2
   323.8 2508.56   331.9  2509.6   347.9 2511.06   355.8 2511.12   365.4 2513.31
     370 2513.68     375 2513.17   446.8 2515.94     500 2516.63   528.9 2518.64
   537.8 2521.52     552 2527.89   571.3 2537.65   589.5    2548   604.2 2555.15
#Mann= 6 ,-1,0
       0     .06       0      30     .12       0     210      .1       0
   293.6    .045       0   331.9     .06       0     440      .1       0
Bank Sta=293.6,331.9
XS Rating Curve= 0 ,0
Exp/Cntr(USF)=0,0
Exp/Cntr=0.3,0.1

Type RM Length L Ch R = 1 ,27320   ,256.1,256.3,254.9
XS GIS Cut Line= 2
2275613.04958356416302.6077842432275154.01189606416688.981180662
#Sta/Elev= 30
       0 2601.38    35.1 2585.27    74.3 2563.34    95.3 2558.57   121.7 2554.39
   127.4 2552.52   152.8 2542.12   168.4 2534.78   194.6 2526.27   202.8 2521.66
     221 2509.12   227.6 2506.67   233.8 2506.14   255.1 2506.72   269.3 2508.25
   286.3  2507.1   304.4 2506.22   308.4 2507.21   314.8 2508.72   328.9 2508.46
   340.3 2510.46   351.4 2509.77   357.3 2510.62   372.4 2510.66     397  2513.1
   482.3 2513.81   499.2 2514.72   508.3 2516.84   525.8  2524.1     600 2560.94
#Mann= 5 ,-1,0
       0      .1       0   286.3    .045       0   308.4      .1       0
     360     .06       0     490      .1       0
#XS Ineff= 2 , 0
                          317.84         2512.19
Permanent Ineff=
       F       F
Bank Sta=286.3,308.4
XS Rating Curve= 0 ,0
Exp/Cntr(USF)=0,0
Exp/Cntr=0.3,0.1

Type RM Length L Ch R = 1 ,27064   ,245.2,245.9,245.3
XS GIS Cut Line= 2
2275477.62943391416104.8067123072275011.70000799416482.840798155
#Sta/Elev= 30
       0  2601.1    12.2 2596.17    27.6 2589.02    63.7 2574.93    86.6 2565.16
   104.9 2558.05   161.6 2541.37   194.7 2529.13   197.6 2527.77   218.2 2514.08
   223.1 2511.18   225.8 2510.22   238.8 2507.47   273.6 2505.34   282.8 2503.07
   300.6  2502.4   310.9 2502.46   314.1 2502.98   321.2 2504.44   336.7 2505.04
     347 2507.57   362.4 2508.59   377.9 2507.81   388.2  2508.6   416.5 2508.55
   506.7 2511.78   533.1 2512.22   555.8 2512.43   578.3 2511.33     600 2512.17
#Mann= 4 ,-1,0
       0      .1       0   282.8    .045       0   314.1     .06       0
     550      .1       0
Bank Sta=282.8,314.1
XS Rating Curve= 0 ,0
Exp/Cntr(USF)=0,0
Exp/Cntr=0.3,0.1

Type RM Length L Ch R = 1 ,26818   ,257.7,260.2,257.3
XS GIS Cut Line= 3
2275297.20807178415916.710030091 2275028.9167302 416172.47283728
2274997.17386059416451.076757365
#Sta/Elev= 30
       0  2571.1    37.8 2563.02    83.1 2550.81   134.1 2535.41   156.2  2527.7
   194.8 2515.29     221  2511.6   226.8 2510.19   239.1 2502.82   244.2  2502.1
   258.5  2502.7   267.3 2501.85   296.3 2502.11   306.6 2501.59   312.3 2500.85
   323.6 2500.73   332.1 2501.42   343.4 2503.51   363.2 2504.33   407.6 2504.83
   423.7 2506.29   455.1 2504.79     468 2506.12   491.2 2505.26   504.2 2506.59
   524.4 2506.95   544.5 2508.61   549.1 2508.03     629 2511.29   651.1 2511.31
#Mann= 7 ,-1,0
       0      .1       0      70     .12       0     210      .1       0
   306.6    .045       0   332.1      .1       0     350     .06       0
  460.67      .1       0
Bank Sta=306.6,332.1
XS Rating Curve= 0 ,0
Exp/Cntr(USF)=0,0
Exp/Cntr=0.3,0.1

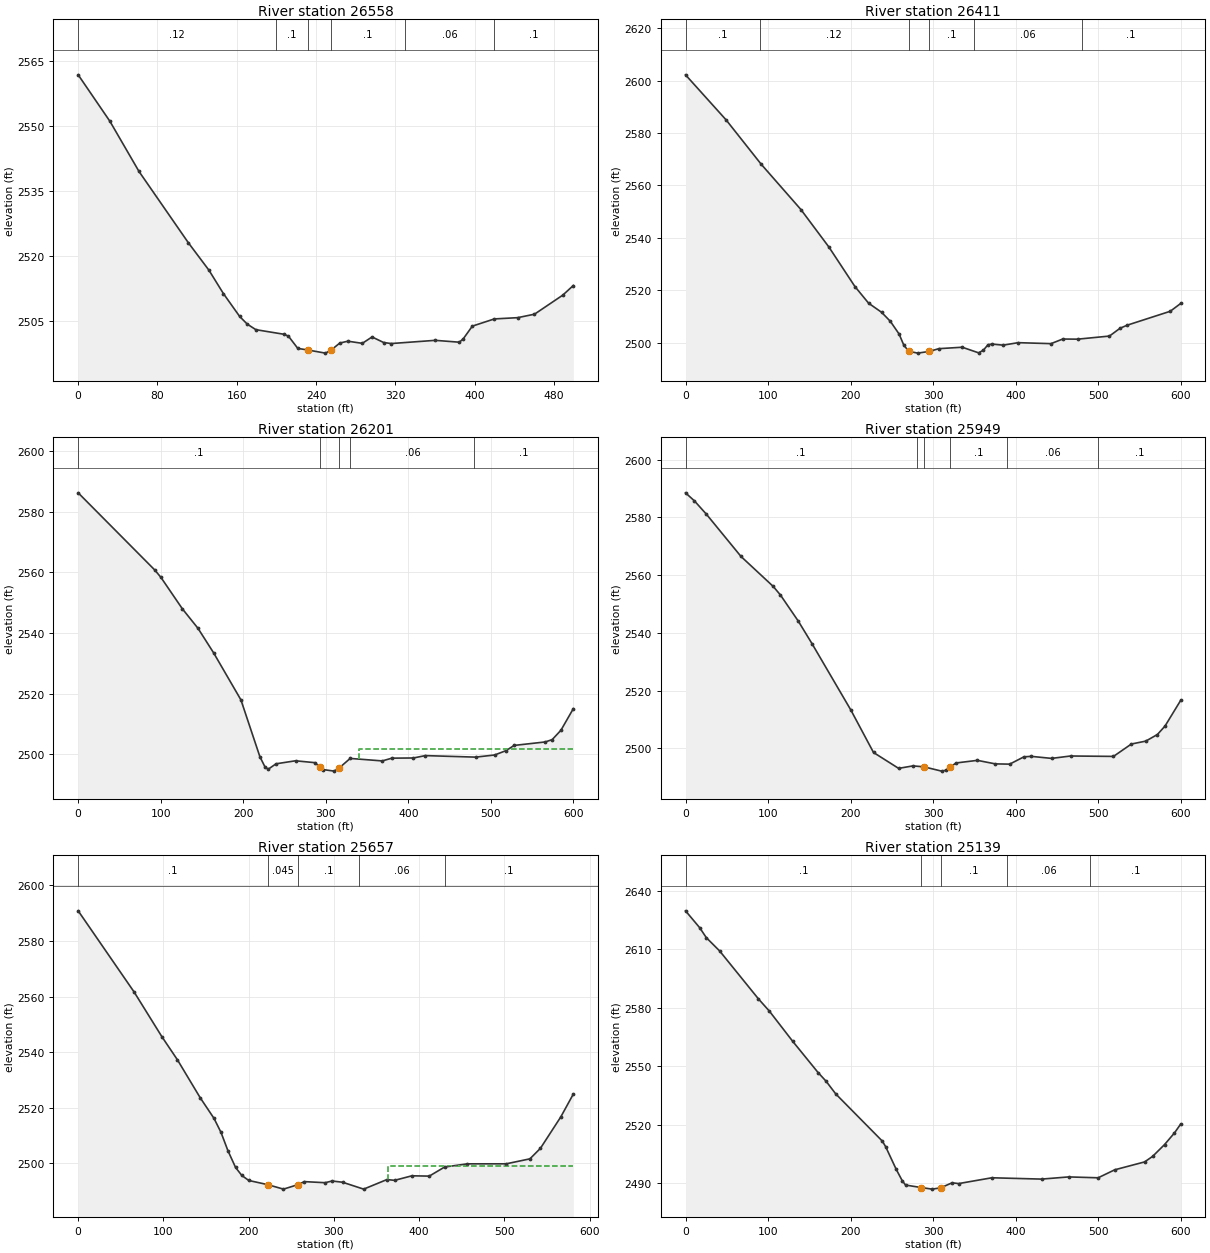
Type RM Length L Ch R = 1 ,26558   ,150.1,146.7,146.2
XS GIS Cut Line= 3
2275091.51711813 415775.353832942274760.50484577416082.961197153
2274713.69502947416092.155982496
#Sta/Elev= 30
       0 2561.82      32 2551.11    61.4 2539.52   111.2 2523.07     132 2516.73
   146.5 2511.37   162.9 2506.09   170.6 2504.31   179.3 2503.03   207.4 2501.98
   212.1 2501.55   221.6 2498.71   231.8 2498.34   249.5 2497.62   255.3 2498.34
     264 2499.95   272.1 2500.37   286.7 2499.88   296.5 2501.35   308.2 2500.07
   315.8 2499.83   360.3 2500.57   384.6 2500.14   388.6 2500.94   397.7 2503.85
   419.9 2505.51   443.4  2505.8   460.4  2506.6   488.9 2510.99499.5798 2513.22
#Mann= 6 ,-1,0
       0     .12       0     200      .1       0   231.8    .045       0
   255.3      .1       0     330     .06       0     420      .1       0
Bank Sta=231.8,255.3
XS Rating Curve= 0 ,0
Exp/Cntr(USF)=0,0
Exp/Cntr=0.3,0.1

Type RM Length L Ch R = 1 ,26411   ,212.7,210.8,206.1
XS GIS Cut Line= 2
2275032.10948559415599.7954387732274633.18968963416047.972854971
#Sta/Elev= 30
       0 2602.22    49.1 2585.05    91.6 2568.14   139.8 2550.83   173.8 2536.49
   205.3 2521.43   221.9 2515.07   237.5 2511.63   248.2 2508.17   258.8 2503.32
   264.6 2499.01   270.6 2496.74   281.4 2496.03   295.6 2496.69   306.9 2497.73
   335.3 2498.28   355.1 2496.15   360.8  2497.1   366.4  2499.2   371.3 2499.49
   384.9 2499.07     403 2500.02   442.9 2499.65   457.1 2501.41   475.2 2501.36
   513.7 2502.54   526.6 2505.53   535.3  2506.7   587.4    2512     600 2514.97
#Mann= 6 ,-1,0
       0      .1       0      90     .12       0   270.6    .045       0
   295.6      .1       0     350     .06       0     480      .1       0
Bank Sta=270.6,295.6
XS Rating Curve= 0 ,0
Exp/Cntr(USF)=0,0
Exp/Cntr=0.3,0.1

Type RM Length L Ch R = 1 ,26201   ,257.9,251.8,245.7
XS GIS Cut Line= 2
2274829.64715462415454.3705617982274509.62593817415961.900286069
#Sta/Elev= 30
       0 2586.24    92.8 2560.78   100.3 2558.33   126.3 2547.95   145.2 2541.53
   164.1 2533.45   197.2 2517.93   220.2 2499.17   226.4 2495.78   230.3 2495.04
   239.8 2496.83   263.4 2497.82     287  2497.2   293.1 2495.67   296.5 2494.94
   310.2 2494.41   316.3 2495.45   329.6  2498.6   368.5 2497.78   380.1 2498.69
   406.2 2498.75   420.7 2499.53   481.6 2499.03   504.6 2499.73   518.8 2501.21
   528.2 2502.89     566 2504.04   574.4 2504.81     585  2507.9     600 2515.02
#Mann= 5 ,-1,0
       0      .1       0   293.1    .045       0   316.3      .1       0
     330     .06       0     480      .1       0
#XS Ineff= 2 , 0
                          339.94         2501.58
Permanent Ineff=
       F       F
Bank Sta=293.1,316.3
XS Rating Curve= 0 ,0
Exp/Cntr(USF)=0,0
Exp/Cntr=0.3,0.1

Type RM Length L Ch R = 1 ,25949   ,288.3,291.6,289.3
XS GIS Cut Line= 2
2274571.29479965415307.2507742612274338.25698536 415860.14622289
#Sta/Elev= 30
       0 2588.48    10.8 2585.69    25.2 2581.11    67.2 2566.45   106.3 2556.06
     115  2553.1   136.7 2544.03   153.5 2536.14   200.4 2513.23   227.8 2498.56
   258.2 2493.06   275.6 2493.91     2892493.587   310.3  2492.1   315.3 2492.38
   320.4 2493.46   327.9 2494.93   353.7 2495.83   375.4 2494.61   392.8 2494.52
   410.1 2497.05   418.8 2497.22   443.6 2496.51   466.6 2497.34   518.6  2497.2
   540.3 2501.49   557.7 2502.49   571.8 2504.78     581 2507.69     600 2516.59
#Mann= 6 ,-1,0
       0      .1       0     280     .06       0     289    .045       0
   320.4      .1       0     390     .06       0     500      .1       0
Bank Sta=289,320.4
XS Rating Curve= 0 ,0
Exp/Cntr(USF)=0,0
Exp/Cntr=0.3,0.1

Type RM Length L Ch R = 1 ,25657   ,516.6,517.9,501.8
XS GIS Cut Line= 2
2274252.05553277415244.6425025372274141.90998823415815.138579169
#Sta/Elev= 30
       0 2590.82    65.7 2561.61    98.3 2545.53   116.5 2537.24   143.1 2523.66
   159.4 2516.19   167.6 2511.16   175.7 2504.59   184.7 2498.55     192 2495.68
   200.2 2493.87   222.3 2492.38   240.9 2490.76   258.3 2492.41   265.3 2493.46
   289.8 2493.07   297.9 2493.68   310.2 2493.24     335 2490.76   362.3  2494.2
   371.3 2493.92   391.6 2495.55     412 2495.44     430 2498.71   456.8 2499.85
   502.3 2499.86   530.1 2501.65   542.4 2505.43   566.3 2516.72     581 2524.94
#Mann= 5 ,-1,0
       0      .1       0   222.3    .045       0   258.3      .1       0
     330     .06       0     430      .1       0
#XS Ineff= 2 , 0
                           363.6         2499.19
Permanent Ineff=
       F       F
Bank Sta=222.3,258.3
XS Rating Curve= 0 ,0
Exp/Cntr(USF)=0,0
Exp/Cntr=0.3,0.1

Type RM Length L Ch R = 1 ,25139   ,210.5,210.4,209.5
XS GIS Cut Line= 2
2273845.46758831415184.1172221342273910.27248681415780.607226351
#Sta/Elev= 30
       0  2629.8    17.2 2621.12    25.2 2616.03    41.3 2609.22    88.4 2584.57
   101.7 2578.26   129.8 2562.85   160.6 2546.79   170.4 2542.28   182.1 2535.77
   238.5 2511.56   242.5 2508.71   255.4 2496.99   262.6 2491.25   266.6 2489.01
   285.62487.727   298.8 2486.91   309.12487.561     323 2490.16     331 2489.76
   371.2 2492.74   431.5 2492.06   464.3 2493.18     500 2492.73   520.1 2496.83
   556.3 2500.88     566 2503.72   580.5 2509.79   592.5 2515.77     600 2520.29
#Mann= 5 ,-1,0
       0      .1       0   285.6    .045       0   309.1      .1       0
     390     .06       0     490      .1       0
Bank Sta=285.6,309.1
XS Rating Curve= 0 ,0
Exp/Cntr(USF)=0,0
Exp/Cntr=0.3,0.1