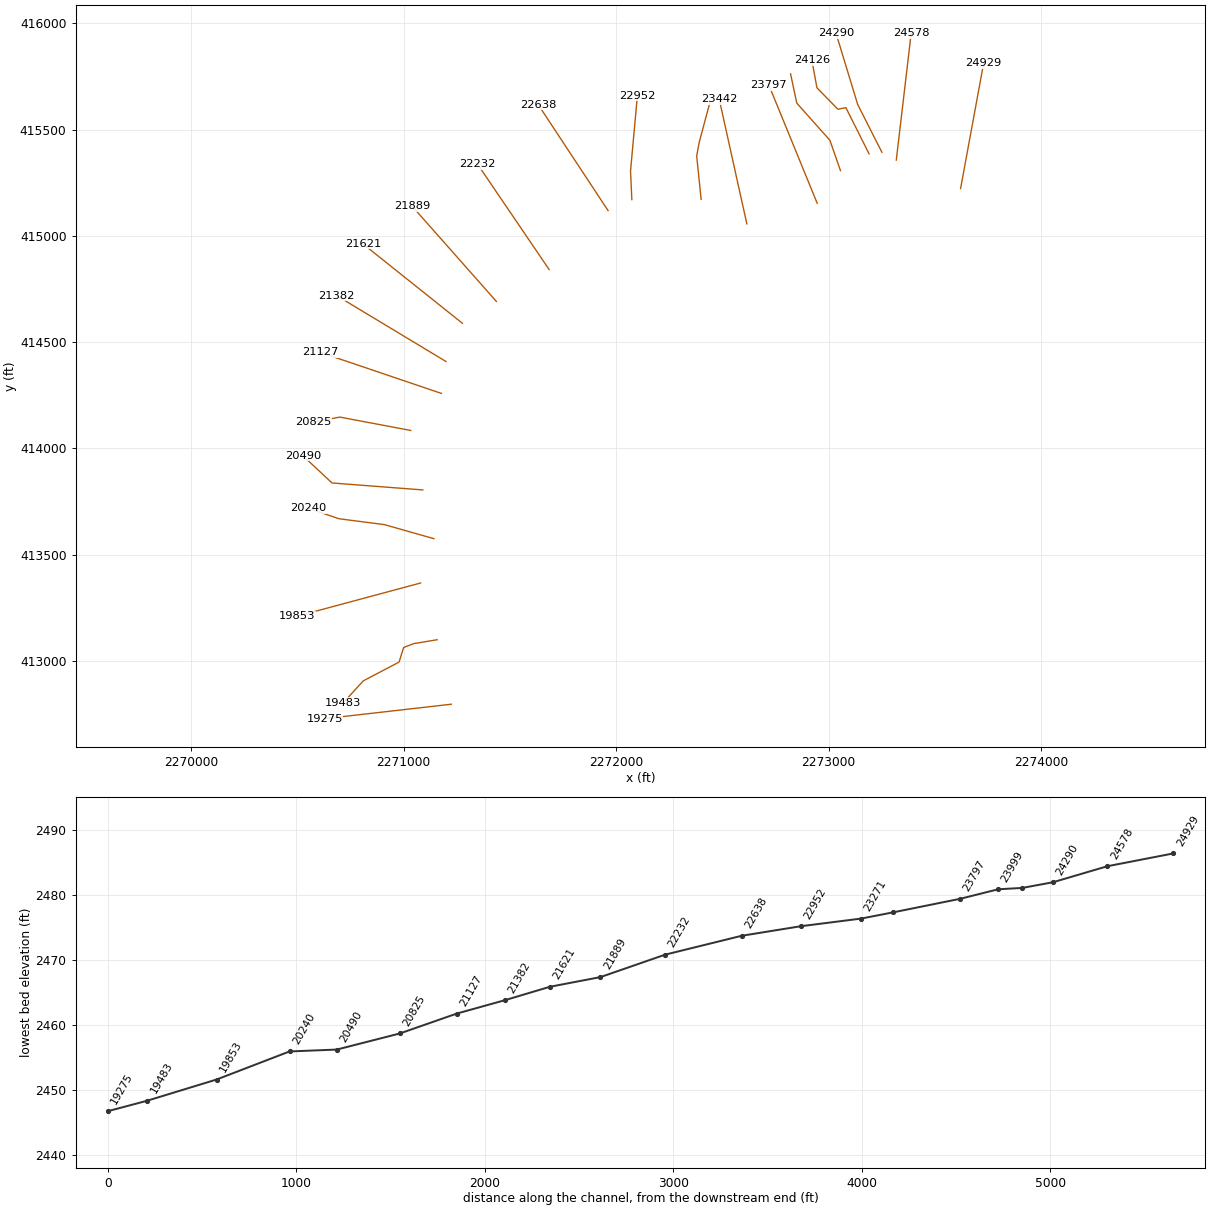
HEC-RAS study LAURELCK.prj: LAURELCK

--- LAURELCK.g01 (geometry) --- (continued)

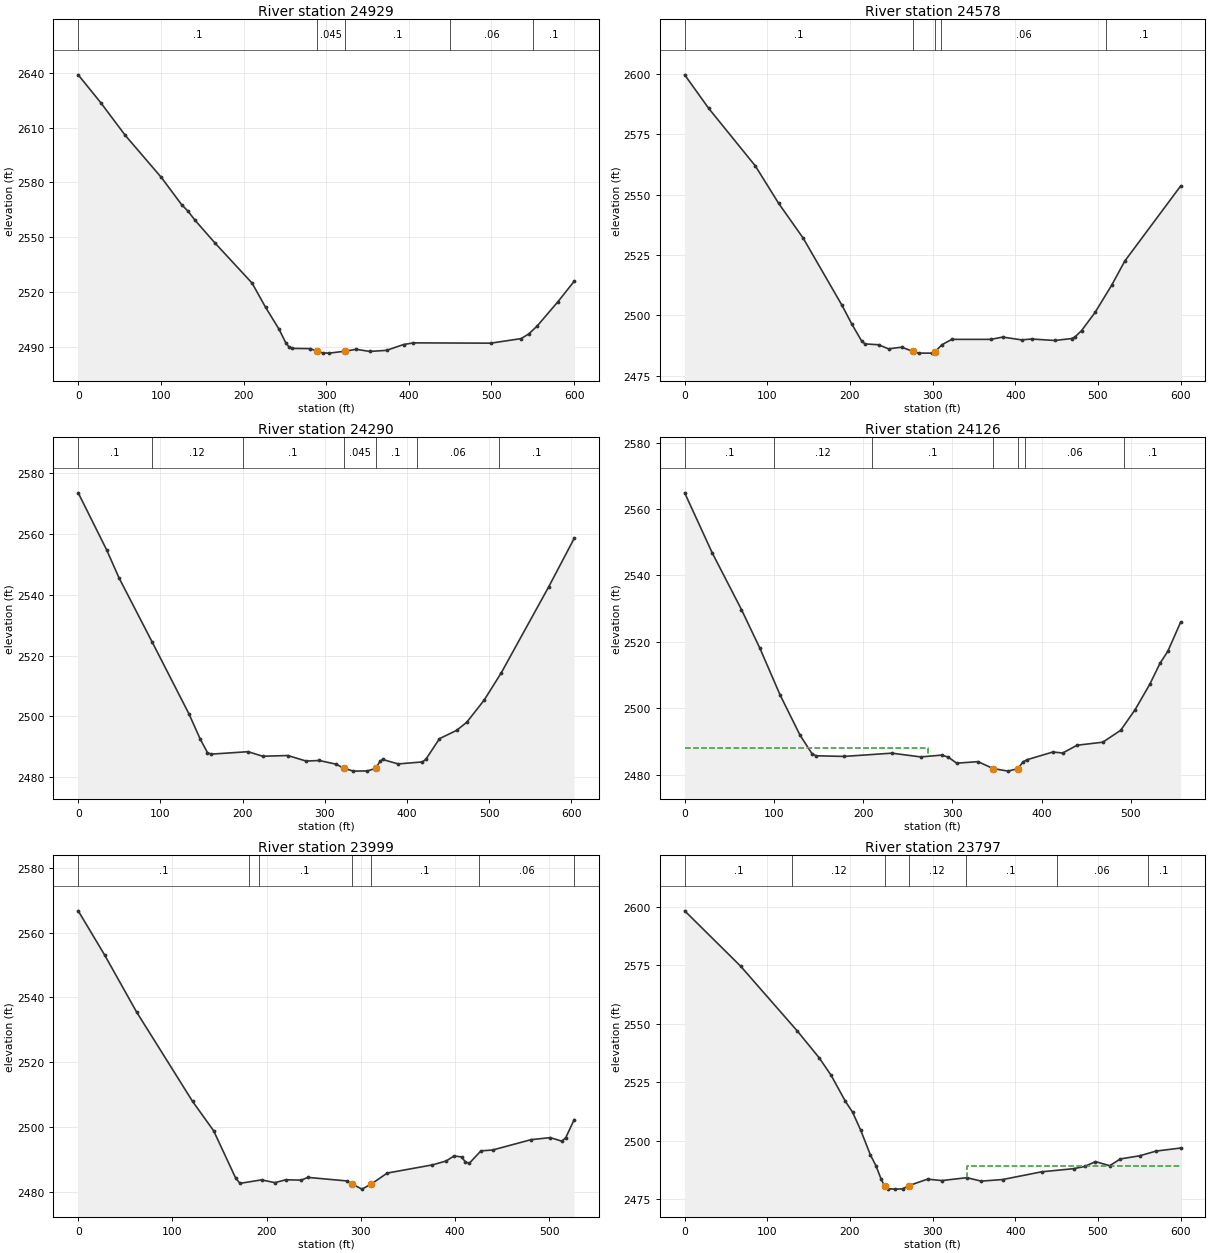
Type RM Length L Ch R = 1 ,24929   ,351.3,350.7,352
XS GIS Cut Line= 2
2273620.66862249415222.2685088392273729.19600577415812.371726148
#Sta/Elev= 30
       0 2639.08    27.4 2623.72      57 2605.82   100.6 2582.76     125 2567.92
   133.1 2564.13   141.2 2559.35   165.6 2546.74   210.4 2524.77   226.6 2511.58
   242.9 2499.53   251.1 2492.08   255.1 2489.73   259.2 2488.96   280.3 2488.85
   288.3 2487.62   295.8 2486.47   303.9 2486.37   323.2 2487.47   336.5 2488.47
   352.7 2487.29   373.1  2487.9   393.7  2491.1   405.6    2492   499.1 2491.84
   535.7 2494.33   544.9 2496.84   555.2 2501.22   580.5 2514.65     600  2525.8
#Mann= 5 ,-1,0
       0      .1       0   288.3    .045       0   323.2      .1       0
     450     .06       0     550      .1       0
Bank Sta=288.3,323.2
XS Rating Curve= 0 ,0
Exp/Cntr(USF)=0,0
Exp/Cntr=0.3,0.1

Type RM Length L Ch R = 1 ,24578   ,273.8,288.7,291.5
XS GIS Cut Line= 2
2273318.05323099415356.2304599052273388.10437553415952.127126407
#Sta/Elev= 30
       0 2599.52    29.1 2585.63    85.5 2561.83   113.7 2546.35   143.3    2532
   190.4 2504.13   202.3 2496.36   214.4 2489.25   218.4 2488.21   234.6 2487.86
   246.6 2486.18   262.7 2486.86   275.92485.113   282.9 2484.41     299  2484.4
     303 2484.97   311.1 2487.86   323.2 2490.09   370.4 2490.09   384.8 2491.04
   407.7 2489.88   419.8 2490.24     448 2489.63   468.2 2490.44   472.2  2491.1
   480.2 2493.74   496.5 2501.24   516.5 2512.44   532.5 2522.51     600 2553.52
#Mann= 5 ,-1,0
       0      .1       0   275.9    .045       0     303      .1       0
     310     .06       0     510      .1       0
Bank Sta=275.9,303
XS Rating Curve= 0 ,0
Exp/Cntr(USF)=0,0
Exp/Cntr=0.3,0.1

Type RM Length L Ch R = 1 ,24290   ,146.7,163,167
XS GIS Cut Line= 3
2273250.50995878415392.8880190372273136.54142236415617.443052233
 2273034.1132686415954.020430227
#Sta/Elev= 30
       0 2573.57    34.7 2554.73    49.6  2545.6      90 2524.45   134.9 2500.73
   148.4 2492.55   157.3 2488.04   161.8 2487.53   206.7 2488.34   224.6 2486.84
   255.1 2487.08   277.5 2485.25   293.4 2485.44   314.3  2484.2322.90342482.903
     335 2481.94   351.9 2482.01362.08322482.852   367.3 2485.19   370.5 2485.77
   389.5 2484.31   418.8 2484.97     423 2485.79   439.7 2492.63   460.6 2495.37
   472.9 2498.03   494.1 2505.34   514.8 2514.27   572.5 2542.56   603.6 2558.55
#Mann= 7 ,-1,0
       0      .1       0      90     .12       0     200      .1       0
322.9034    .045       0362.0832      .1       0  411.82     .06       0
  511.82      .1       0
Bank Sta=322.9034,362.0832
XS Rating Curve= 0 ,0
Exp/Cntr(USF)=0,0
Exp/Cntr=0.3,0.1

Type RM Length L Ch R = 1 ,24126   ,128.1,127.7,126.2
XS GIS Cut Line= 5
2273189.96170506415385.608057873 2273080.8781153415603.022936764
2273043.26308435415595.4999305742272944.71170326415696.308213519
2272920.63808345415827.208521225
#Sta/Elev= 30
       0 2564.87    30.8 2546.83    63.6 2529.73    84.3 2518.05   106.9 2504.02
   129.2 2491.92   142.7 2486.31   147.2 2485.69   178.5  2485.5   232.2 2486.48
   264.4 2485.35   287.8 2485.89   295.1 2485.33   304.8 2483.46   328.7 2483.93
   345.5 2481.85   362.3 2481.07   373.5 2481.85     379  2483.8   383.3 2484.48
   412.6 2486.83   423.5 2486.52   439.7 2488.87   468.5 2489.78   488.5 2493.36
   504.8 2499.62   521.1 2507.22   532.6 2513.55   541.4 2517.19555.6788 2525.92
#Mann= 7 ,-1,0
       0      .1       0     100     .12       0     210      .1       0
   345.5    .045       0   373.5      .1       0  381.61     .06       0
  492.58      .1       0
#XS Ineff= 2 , 0
          273.13 2488.01
Permanent Ineff=
       F       F
Bank Sta=345.5,373.5
XS Rating Curve= 0 ,0
Exp/Cntr(USF)=0,0
Exp/Cntr=0.3,0.1

Type RM Length L Ch R = 1 ,23999   ,210.3,201.4,191.5
XS GIS Cut Line= 4
  2273055.436354415306.616405453 2273005.6480534415449.553610488
2272849.92182527415624.0873540952272820.54851874415761.907535507
#Sta/Elev= 30
       0 2566.71    28.1 2553.05      62 2535.47   121.3 2507.94   143.7 2498.86
   166.9 2484.37   171.6 2482.64   194.6 2483.72   208.8 2482.85   220.1 2483.75
   236.6 2483.64   243.7 2484.48   284.9 2483.39   290.2 2482.52     301 2480.86
   310.8 2482.39   327.8 2485.81   375.9 2488.34   390.5 2489.55   398.7  2491.1
   406.8 2490.79   410.9  2489.2     415 2488.85   427.3 2492.67   439.6 2492.92
   480.5 2496.12   500.9 2496.75   513.2 2495.65   517.3 2496.74   526.2 2502.29
#Mann= 7 ,-1,0
       0      .1       0  181.36     .12       0  191.36      .1       0
   290.2    .045       0   310.8      .1       0  425.27     .06       0
  526.18      .1       0
Bank Sta=290.2,310.8
XS Rating Curve= 0 ,0
Exp/Cntr(USF)=0,0
Exp/Cntr=0.3,0.1

Type RM Length L Ch R = 1 ,23797   ,356.4,355.3,347.5
XS GIS Cut Line= 2
2272945.80238989415153.1969680842272718.68327311415708.549925034
#Sta/Elev= 30
       0 2598.31    67.7 2574.66   136.2 2546.99   162.8 2535.48   177.2 2528.01
   194.5 2516.88   203.1 2512.29   212.9 2504.63   224.7 2493.99   231.3 2489.47
   237.7 2483.67     242 2480.61   246.3 2479.54     255  2479.4   263.6 2479.52
   271.1 2480.89   293.8 2483.66   311.1 2483.06   341.4 2484.29   358.7 2482.82
   384.6  2483.5   432.1 2486.81   470.5 2488.14     484 2489.08     497 2491.16
   514.2 2489.41   527.2 2492.31   550.3 2493.63   570.4 2495.66     600 2496.96
#Mann= 7 ,-1,0
       0      .1       0     130     .12       0     242    .045       0
   271.1     .12       0     340      .1       0     450     .06       0
     560      .1       0
#XS Ineff= 2 , 0
                          341.18         2489.35
Permanent Ineff=
       F       F
Bank Sta=242,271.1
XS Rating Curve= 0 ,0
Exp/Cntr(USF)=0,0
Exp/Cntr=0.3,0.1

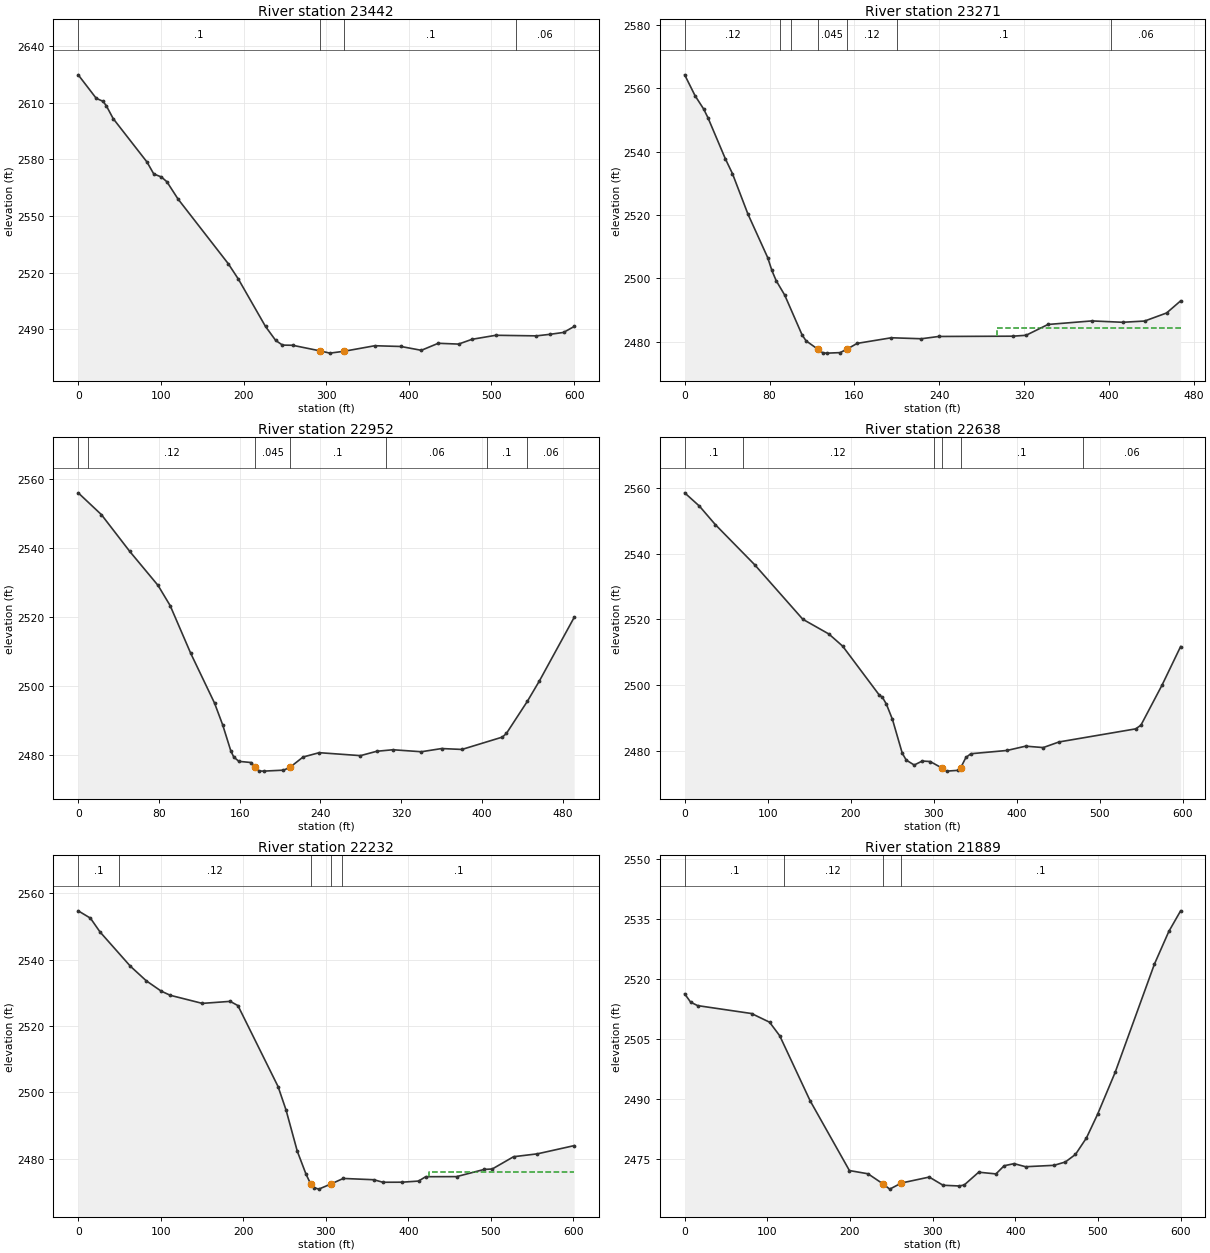
Type RM Length L Ch R = 1 ,23442   ,172.8,170.8,168.3
XS GIS Cut Line= 2
2272614.88008994415055.9255311252272485.10538155415641.722872414
#Sta/Elev= 30
       0 2624.82    21.8 2612.37      30 2610.78    34.1 2608.36    42.3 2601.62
    83.2 2578.61    91.4 2572.29   100.6 2570.68   107.3 2568.15   120.7 2559.03
   181.6 2524.68   193.8 2516.53   226.6 2491.44   238.9 2484.06   247.1 2481.58
   259.4 2481.48   292.8 2478.49   304.5 2477.32   321.9 2478.32   358.8 2481.24
   390.5 2480.84   415.1 2478.81   435.6 2482.54   460.1 2482.11   476.5 2484.65
   505.2 2486.78   554.4 2486.47   570.8 2487.29   587.2 2488.29     600 2491.44
#Mann= 4 ,-1,0
       0      .1       0   292.8    .045       0   321.9      .1       0
     530     .06       0
Bank Sta=292.8,321.9
XS Rating Curve= 0 ,0
Exp/Cntr(USF)=0,0
Exp/Cntr=0.3,0.1

Type RM Length L Ch R = 1 ,23271   ,323.1,319,316.5
XS GIS Cut Line= 4
2272399.73721247415171.4110145022272378.80839468415375.546501329
2272391.01844768415441.2783036792272441.68517771 415629.97358021
#Sta/Elev= 30
       0 2564.23     9.8 2557.63    17.9 2553.43    21.9 2550.71    38.3 2537.74
      45 2533.06    59.6 2520.28    78.2 2506.55    82.2 2502.45    86.2 2499.26
    94.3 2494.67   110.6 2482.15   114.4 2480.24   125.2 2477.67   130.4 2476.41
   134.5 2476.36   146.5 2476.52   152.6 2477.55   162.6 2479.44   194.8 2481.21
   223.1  2480.9   239.4 2481.62   309.2 2481.71   321.7 2481.99   342.4 2485.41
   383.8 2486.53   412.8  2486.1   433.5 2486.49   454.2 2489.04   467.4 2492.86
#Mann= 7 ,-1,0
       0     .12       0      90      .1       0     100     .12       0
   125.2    .045       0   152.6     .12       0     200      .1       0
  402.06     .06       0
#XS Ineff= 2 , 0
                          294.74         2484.38
Permanent Ineff=
       F       F
Bank Sta=125.2,152.6
XS Rating Curve= 0 ,0
Exp/Cntr(USF)=0,0
Exp/Cntr=0.3,0.1

Type RM Length L Ch R = 1 ,22952   ,302.5,314.2,322.6
XS GIS Cut Line= 3
2272073.67203596415170.1743421662272067.52918151 415305.11189164
2272099.78893622415659.977541053
#Sta/Elev= 30
       0 2556.04      23  2549.7    51.1 2539.01    79.1 2529.14    91.1 2523.28
   111.5  2509.4   135.1 2494.94   143.2 2488.58   151.2 2481.08   154.1  2479.3
   159.2 2478.03   171.3 2477.69   175.3 2476.28   179.3 2475.23   183.6 2475.19
   203.4 2475.47  209.71 2476.27   222.8 2479.29   238.8 2480.55   279.7 2479.69
   295.8 2480.96   311.9  2481.4     340 2480.82   360.1 2481.75   380.2 2481.49
   420.3 2485.08   424.3 2486.15     445 2495.46     457 2501.41   491.4 2519.84
#Mann= 7 ,-1,0
       0      .1       0      10     .12       0   175.3    .045       0
  209.71      .1       0  305.08     .06       0  405.08      .1       0
  445.08     .06       0
Bank Sta=175.3,209.71
XS Rating Curve= 0 ,0
Exp/Cntr(USF)=0,0
Exp/Cntr=0.3,0.1

Type RM Length L Ch R = 1 ,22638   ,406.5,406,406.7
XS GIS Cut Line= 2
2271961.95374173 415118.352715582271633.09282099415617.046770314
#Sta/Elev= 30
       0 2558.53    17.8 2554.47    36.9 2548.85    84.2 2536.65   142.3    2520
   173.7 2515.51   190.3 2511.81   234.3 2496.94   238.2 2496.22     243 2494.12
   250.3 2489.47   262.1 2479.18   266.9 2477.08   276.5 2475.58   286.1 2476.79
   295.7 2476.65   309.4 2474.74   315.7 2473.72   329.2 2473.96   332.5 2474.77
   338.8 2477.89   344.7 2479.02   388.3 2480.02   410.7 2481.33   431.9  2480.9
   450.9 2482.61   543.3  2486.6   549.6 2487.73     575 2499.92   597.4 2511.69
#Mann= 6 ,-1,0
       0      .1       0      70     .12       0     300      .1       0
   309.4    .045       0   332.5      .1       0     480     .06       0
Bank Sta=309.4,332.5
XS Rating Curve= 0 ,0
Exp/Cntr(USF)=0,0
Exp/Cntr=0.3,0.1

Type RM Length L Ch R = 1 ,22232   ,339.6,342.7,343.9
XS GIS Cut Line= 2
2271684.64486292414840.9141501812271347.04140588415337.854851053
#Sta/Elev= 30
       0 2554.71    14.8  2552.5    26.4 2548.35    63.2 2538.01    82.5 2533.61
   100.5 2530.51   111.5 2529.25   150.3 2526.81   184.1 2527.42   193.5 2526.14
   242.1 2501.74   251.8 2494.65   265.4 2482.25     276 2475.31281.55822472.418
   285.6 2471.28   291.4 2470.82   305.8 2472.33   321.1 2474.04   358.2 2473.65
   369.1 2472.89   392.3 2472.91   412.3 2473.25   420.9 2474.56   458.4 2474.59
     492 2476.77   501.6 2476.89   527.4 2480.59   556.3 2481.46   600.8 2483.93
#Mann= 5 ,-1,0
       0      .1       0      50     .12       0281.5582    .045       0
   305.8     .12       0     320      .1       0
#XS Ineff= 2 , 0
                          424.42         2476.11
Permanent Ineff=
       F       F
Bank Sta=281.5582,305.8
XS Rating Curve= 0 ,0
Exp/Cntr(USF)=0,0
Exp/Cntr=0.3,0.1

Type RM Length L Ch R = 1 ,21889   ,261.2,268.7,267
XS GIS Cut Line= 2
2271436.19799224414691.0447522562271038.71835482415140.499908899
#Sta/Elev= 30
       0 2516.27     7.2 2514.18    15.7 2513.32    80.9 2511.34   102.7 2509.17
     115 2505.77   151.7 2489.53   199.3 2472.03   221.8 2471.22   239.6 2468.74
   248.1 2467.38   262.2 2468.91   295.9  2470.4   312.6 2468.35   332.1 2468.17
   338.2 2468.42   355.7 2471.62   376.6 2471.19   386.5 2473.23   398.5 2473.76
   412.4 2472.99   446.9 2473.34   460.6 2474.18   472.8 2476.07   486.1 2480.21
   499.5  2486.1   520.8 2496.61   568.3 2523.71   585.7 2531.88     600 2537.05
#Mann= 4 ,-1,0
       0      .1       0     120     .12       0   239.6    .045       0
   262.2      .1       0
Bank Sta=239.6,262.2
XS Rating Curve= 0 ,0
Exp/Cntr(USF)=0,0
Exp/Cntr=0.3,0.1

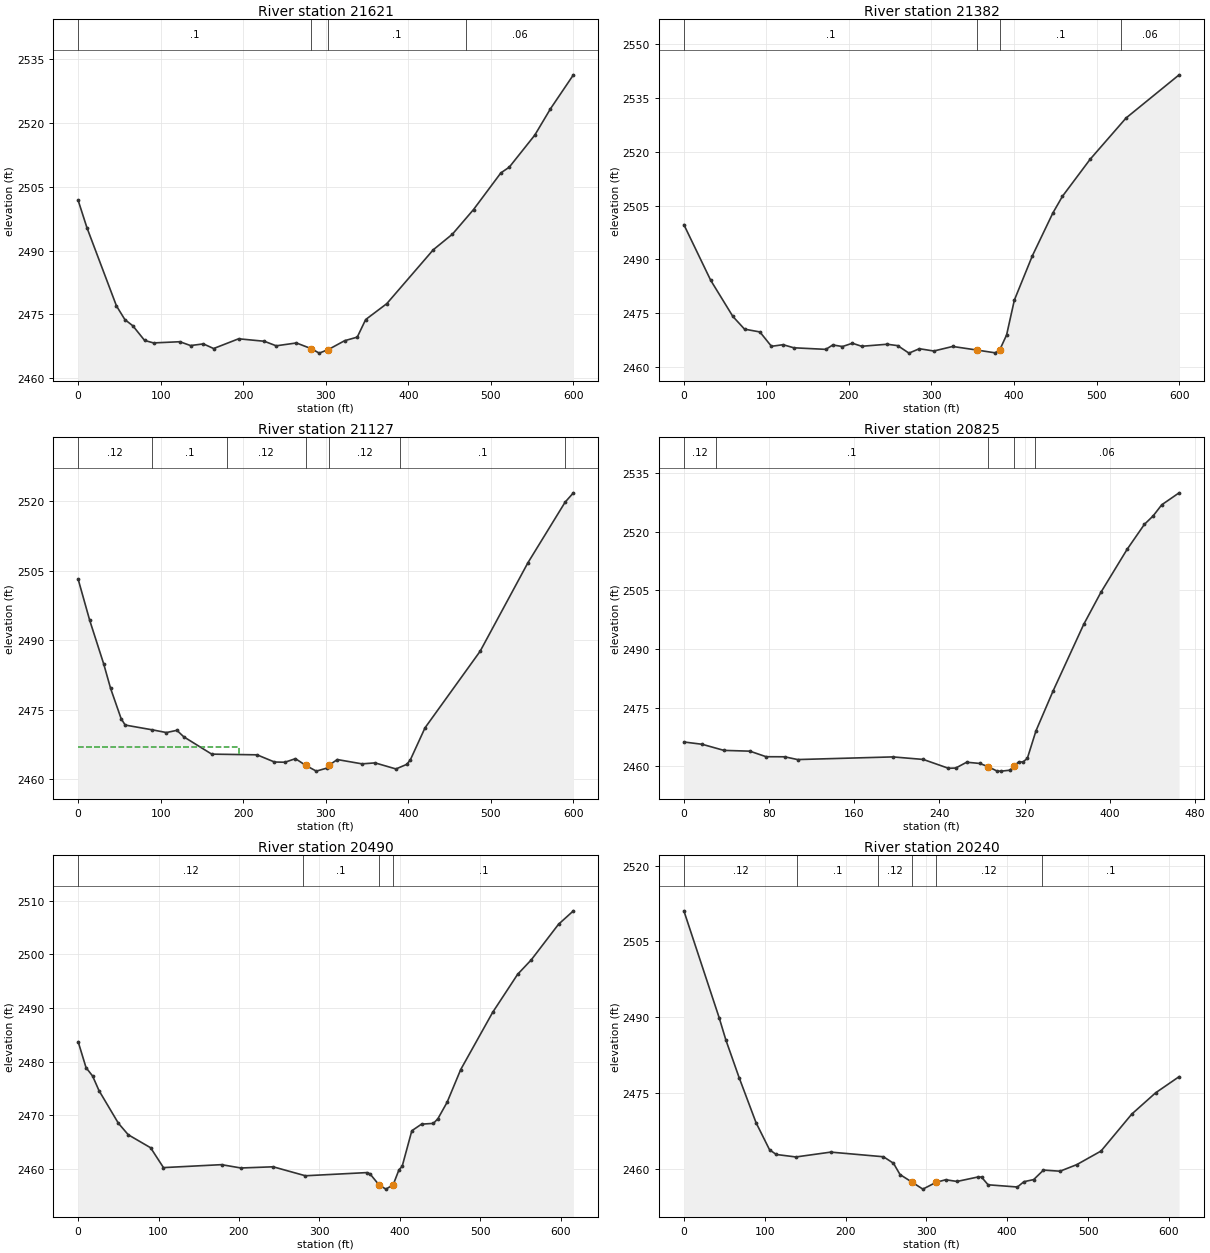
Type RM Length L Ch R = 1 ,21621   ,235.7,238.6,241.4
XS GIS Cut Line= 2
2271276.45287878414588.264547256 2270807.4635717414962.495799087
#Sta/Elev= 30
       0 2501.78    10.6 2495.38    46.4 2476.98    56.6 2473.77    66.3  2472.3
    80.5 2468.87    91.3 2468.29   123.2 2468.57   136.1 2467.67   151.7 2468.06
   164.1 2466.97   194.4 2469.26   225.5 2468.68   239.9 2467.61   264.4 2468.28
   282.6 2466.92     292 2465.89   302.9 2466.71   322.8 2468.81   338.1 2469.65
   348.3 2473.78   373.9 2477.52   430.2 2490.18   453.4 2493.85     479 2499.64
   512.1 2508.25   522.3  2509.6   553.2 2517.13   572.2 2523.32     600  2531.3
#Mann= 4 ,-1,0
       0      .1       0   282.6    .045       0   302.9      .1       0
     470     .06       0
Bank Sta=282.6,302.9
XS Rating Curve= 0 ,0
Exp/Cntr(USF)=0,0
Exp/Cntr=0.3,0.1

Type RM Length L Ch R = 1 ,21382   ,249.6,254.7,257.1
XS GIS Cut Line= 2
2271199.08387454414408.3987378362270685.20359784414718.119678728
#Sta/Elev= 30
       0 2499.68    32.5 2484.15    59.4 2474.05    73.5 2470.52    92.1 2469.74
   106.1 2465.73   120.2 2466.18   133.2 2465.32     172 2464.88   180.4 2466.11
   192.1 2465.67   204.2 2466.59   215.4 2465.74   246.3 2466.31   259.1 2465.92
   272.7 2463.83   285.3 2465.06   302.8 2464.42   325.7 2465.69   355.3 2464.68
     377 2463.92   382.4  2464.6     391  2468.9   400.4 2478.63   422.3 2491.03
   447.1 2502.95   458.7  2507.6   492.2 2517.91   535.8 2529.44     600 2541.47
#Mann= 4 ,-1,0
       0      .1       0   355.3    .045       0   382.4      .1       0
     530     .06       0
Bank Sta=355.3,382.4
XS Rating Curve= 0 ,0
Exp/Cntr(USF)=0,0
Exp/Cntr=0.3,0.1

Type RM Length L Ch R = 1 ,21127   ,300.2,302.7,303.7
XS GIS Cut Line= 2
2271177.43888201 414258.296409482270609.18612847414450.880957411
#Sta/Elev= 30
       0  2503.2      14 2494.32    30.9 2484.94    39.3 2479.63      52 2473.13
    56.9 2471.73      90 2470.69   106.9 2470.11   119.6 2470.59     128 2469.18
   161.8 2465.45   216.7  2465.3   237.8 2463.75   250.5  2463.7   263.2 2464.47
   275.9    2463   288.5 2461.78   301.2 2462.43   304.1 2463.07   313.9 2464.28
   343.9 2463.35   359.7 2463.56     385 2462.25   398.3 2463.26   402.6 2464.28
   420.2 2471.13     487 2487.67   544.8 2506.75     590 2519.87     600 2521.87
#Mann= 7 ,-1,0
       0     .12       0      90      .1       0     180     .12       0
   275.9    .045       0   304.1     .12       0     390      .1       0
     590     .06       0
#XS Ineff= 2 , 0
          195.06 2467.07
Permanent Ineff=
       F       F
Bank Sta=275.9,304.1
XS Rating Curve= 0 ,0
Exp/Cntr(USF)=0,0
Exp/Cntr=0.3,0.1

Type RM Length L Ch R = 1 ,20825   ,332.1,334.2,334.8
XS GIS Cut Line= 3
2271033.10683412414083.9834609572270699.59856714414146.809882529
2270576.12852853414123.479244158
#Sta/Elev= 30
       0 2466.18    17.2 2465.59    37.6 2464.03      62 2463.83    77.2 2462.41
    94.6 2462.39   106.8 2461.68   196.3 2462.36   224.8 2461.71   248.4 2459.45
   255.3 2459.51   265.5    2461   277.7 2460.69   285.5 2459.89     294 2458.74
   298.1 2458.72   306.2 2458.96   310.1 2460.04   314.4  2461.1   318.4 2461.06
   322.5 2461.99   330.6 2469.03   346.6  2479.2   375.4 2496.27   391.6  2504.5
   416.1 2515.46   432.4 2521.88   440.6 2524.04   448.7 2526.89     465 2529.95
#Mann= 5 ,-1,0
       0     .12       0      30      .1       0   285.5    .045       0
   310.1      .1       0     330     .06       0
Bank Sta=285.5,310.1
XS Rating Curve= 0 ,0
Exp/Cntr(USF)=0,0
Exp/Cntr=0.3,0.1

Type RM Length L Ch R = 1 ,20490   ,262.5,250.8,251.7
XS GIS Cut Line= 3
2271089.98400087413804.0959019892270662.76613606  413836.8271355
2270525.78992533413964.839968002
#Sta/Elev= 30
       0 2483.71     9.8 2478.88    17.9 2477.34    25.9 2474.61      50 2468.53
    62.3 2466.38    90.1 2463.96   106.1 2460.26   178.3 2460.81   202.4 2460.19
   242.5 2460.41   282.6 2458.74   358.9 2459.33   362.9 2459.11   374.4    2457
   382.8 2456.25   391.8 2457.06     399 2459.85     403  2460.5     415 2467.13
   427.1 2468.36   441.9  2468.5   447.5 2469.39   458.9 2472.44   475.8 2478.53
   515.5 2489.18   546.6 2496.28   563.6 2498.98   597.5 2505.61     616 2508.11
#Mann= 4 ,-1,0
       0     .12       0     280      .1       0   374.4    .045       0
   391.8      .1       0
Bank Sta=374.4,391.8
XS Rating Curve= 0 ,0
Exp/Cntr(USF)=0,0
Exp/Cntr=0.3,0.1

Type RM Length L Ch R = 1 ,20240   ,377.5,387,395.4
XS GIS Cut Line= 4
2271142.12060507413574.722654282 2270908.8879412413640.934270189
2270695.41494695413668.5601870922270548.79044513413718.424490363
#Sta/Elev= 30
       0 2511.07    43.6 2489.93    51.9 2485.52    68.3 2478.06    89.3 2469.11
     106 2463.75   114.3 2462.82   138.6 2462.33   181.7 2463.29   246.9 2462.37
   259.3 2461.08   267.4 2458.84282.4482 2457.32   295.6 2455.96   311.7 2457.28
   323.8 2457.82   337.9 2457.48   364.2 2458.38   368.2 2458.34   376.3 2456.82
   412.6 2456.38   420.6 2457.43   432.7 2457.85   444.8 2459.73   465.3 2459.51
     486 2460.81     516  2463.5   554.1 2470.83   583.6 2475.04   612.6 2478.23
#Mann= 6 ,-1,0
       0     .12       0     140      .1       0     240     .12       0
282.4482    .045       0   311.7     .12       0  442.45      .1       0
Bank Sta=282.4482,311.7
XS Rating Curve= 0 ,0
Exp/Cntr(USF)=0,0
Exp/Cntr=0.3,0.1

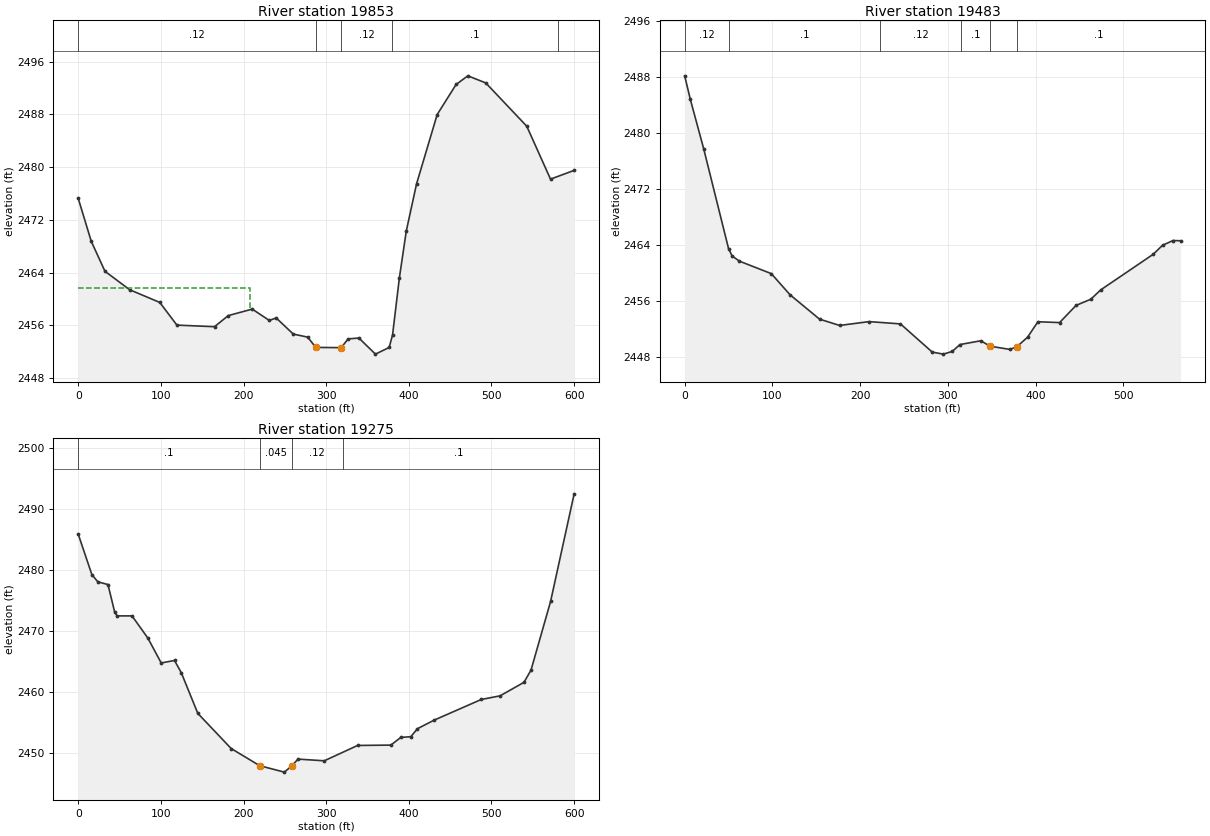
Type RM Length L Ch R = 1 ,19853   ,366.8,369.9,375.3
XS GIS Cut Line= 2
 2271079.4491621 413366.083629352270500.02182605 413210.31469074
#Sta/Elev= 30
       0 2475.28    15.8 2468.75    32.4 2464.21    62.2 2461.42    98.7 2459.49
   119.4 2456.05   164.9 2455.81   181.5 2457.49   210.5 2458.48   231.2 2456.76
   239.5 2457.14   260.2 2454.69   277.6 2454.23   287.4 2452.67   318.2 2452.63
   326.5 2453.96   339.6 2454.09   359.6 2451.65   376.2 2452.66   380.3 2454.56
   388.6 2463.26   396.9 2470.31   409.3 2477.46   434.3 2487.99   457.2 2492.55
   471.4 2493.86   493.1 2492.78   542.7 2486.21   571.4 2478.19     600 2479.52
#Mann= 5 ,-1,0
       0     .12       0   287.4    .045       0   318.2     .12       0
     380      .1       0     580     .06       0
#XS Ineff= 2 , 0
          207.55 2461.74
Permanent Ineff=
       F       F
Bank Sta=287.4,318.2
XS Rating Curve= 0 ,0
Exp/Cntr(USF)=0,0
Exp/Cntr=0.3,0.1

Type RM Length L Ch R = 1 ,19483   ,219.7,208,200.5
XS GIS Cut Line= 6
2271157.50440899413099.2443835472271046.73956428413080.791838509
  2270999.756855413062.437418831 2270978.2755397412993.943735324
2270809.87576598412905.5791279022270715.07551516412802.035719832
#Sta/Elev= 30
       0 2488.17     6.4 2484.82    21.6 2477.77      50 2463.46    54.1 2462.41
    62.4 2461.67    98.7 2459.89   120.1 2456.86   153.7 2453.38   176.6 2452.48
   210.2 2453.03   245.9  2452.7   282.1 2448.67   294.7 2448.38   304.8 2448.76
   313.7 2449.75   337.4 2450.29   348.1 2449.51   370.8 2449.05   378.8 2449.47
   390.7  2450.8   402.5 2453.01   427.2 2452.89     446 2455.35   462.8 2456.23
     474 2457.56   533.8 2462.65   544.5 2463.94   556.4 2464.62   565.1 2464.59
#Mann= 6 ,-1,0
       0     .12       0      50      .1       0  222.73     .12       0
  314.52      .1       0   348.1    .045       0   378.8      .1       0
Bank Sta=348.1,378.8
XS Rating Curve= 0 ,0
Exp/Cntr(USF)=0,0
Exp/Cntr=0.3,0.1

Type RM Length L Ch R = 1 ,19275   ,372.1,373.4,365
XS GIS Cut Line= 2
2271223.96803229412795.6140268012270627.81748628412727.757365409
#Sta/Elev= 30
       0 2485.87    16.5 2479.23    23.7 2478.04      36 2477.59    44.1 2473.08
      47 2472.44    65.1 2472.44    84.3 2468.79   100.4 2464.71   116.5 2465.12
   124.6 2463.14   144.7 2456.43     185 2450.66  219.662447.829   249.4 2446.78
   258.6 2447.83   265.9 2448.92   297.7 2448.64     338 2451.16   378.2 2451.22
   390.3 2452.48   402.4  2452.6   410.4 2453.91   430.6 2455.32   487.6 2458.71
   510.4 2459.31   539.3 2461.53   547.8 2463.53   571.5 2474.82     600 2492.49
#Mann= 4 ,-1,0
       0      .1       0  219.66    .045       0   258.6     .12       0
     320      .1       0
Bank Sta=219.66,258.6
XS Rating Curve= 0 ,0
Exp/Cntr(USF)=0,0
Exp/Cntr=0.3,0.1