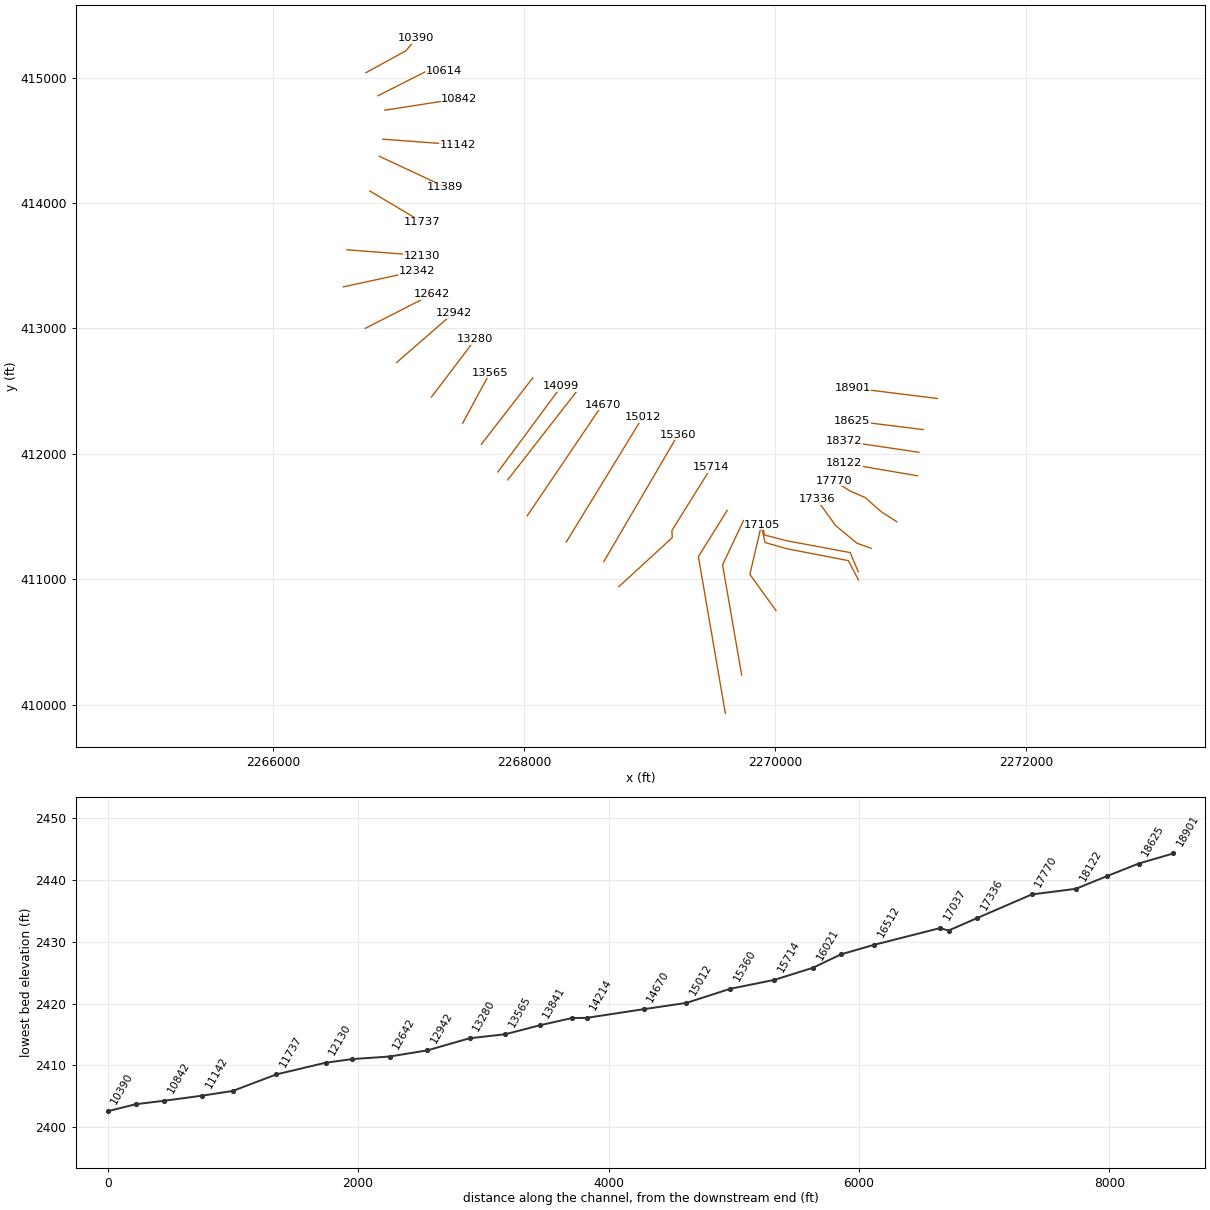
HEC-RAS study LAURELCK.prj: LAURELCK

--- LAURELCK.g01 (geometry) --- (continued)

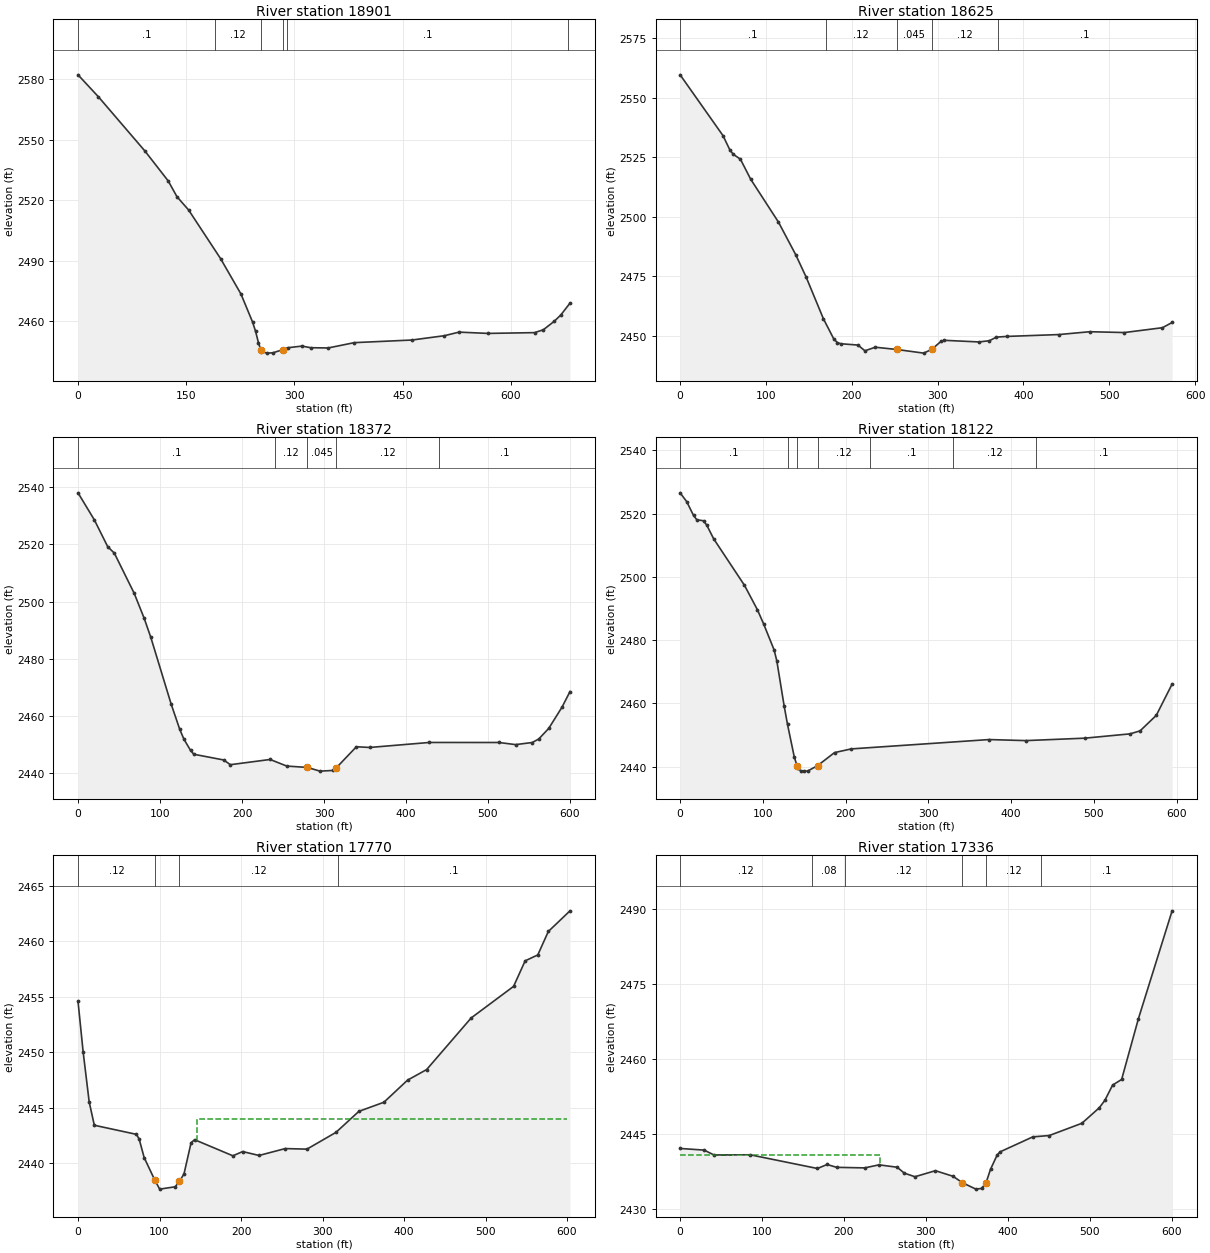
Type RM Length L Ch R = 1 ,18901   ,274.3,276.7,278.3
XS GIS Cut Line= 2
2271292.37267281412440.9995780642270615.46376301412524.822294989
#Sta/Elev= 30
       0 2582.13    28.4 2571.21    92.9 2544.35   125.1 2529.57   137.2 2521.78
   153.4 2515.18   197.7 2491.11   225.9 2473.62     242 2459.74   246.1 2455.23
   250.1  2449.6  253.262446.046   254.1  2445.1   262.2 2444.34   270.2  2444.5
   283.7 2446.03   290.8 2447.01   310.6 2447.83   322.6 2447.02   346.8  2446.9
   383.1 2449.53     463 2450.83     508 2452.97   528.2 2454.74   568.5  2454.1
     633 2454.49   645.1  2455.9   660.2 2460.08   669.3  2463.2   682.1 2469.09
#Mann= 6 ,-1,0
       0      .1       0     190     .12       0  253.26    .045       0
   283.7     .12       0     290      .1       0     680     .06       0
Bank Sta=253.26,283.7
XS Rating Curve= 0 ,0
Exp/Cntr(USF)=0,0
Exp/Cntr=0.3,0.1

Type RM Length L Ch R = 1 ,18625   ,250.9,252.6,244.8
XS GIS Cut Line= 2
2271177.81415239412192.8445889772270609.01481803412263.956110231
#Sta/Elev= 30
       0 2559.68      50  2534.1    58.1    2528    62.1 2526.22    70.2 2524.25
    82.3 2515.75   114.5 2497.82   134.7 2484.06   146.8 2474.69   166.9 2457.18
     179 2448.67   183.1 2447.15   187.1 2446.65   207.2 2446.09   215.3 2443.68
   227.4 2445.18 252.103 2444.25   283.8  2442.7293.00232444.253     304 2447.64
     308 2448.08   348.3  2447.4   360.4 2447.93   368.5 2449.43   380.6 2449.72
     441  2450.5   477.3  2451.7   517.6 2451.35     562 2453.39   573.2 2455.58
#Mann= 5 ,-1,0
       0      .1       0     170     .12       0 252.103    .045       0
293.0023     .12       0     370      .1       0
Bank Sta=252.103,293.0023
XS Rating Curve= 0 ,0
Exp/Cntr(USF)=0,0
Exp/Cntr=0.3,0.1

Type RM Length L Ch R = 1 ,18372   ,250.9,250.1,257.7
XS GIS Cut Line= 2
2271143.95341983412011.858012748 2270550.5318827412100.463200319
#Sta/Elev= 30
       0 2538.06      20 2528.55    36.2 2519.22    44.3 2516.95    68.5 2502.91
    80.7 2494.15    88.8 2487.46   113.6 2464.12   124.1 2455.26   129.2 2451.83
   137.3 2447.89   141.3 2446.57   177.7 2444.57   185.8 2442.92   234.3 2444.75
   254.6 2442.44   279.8 2441.96     295 2440.67   311.2 2440.91   315.2 2441.89
   339.5  2449.2   355.7 2448.95   428.5  2450.7   513.4 2450.69   533.6 2449.95
   553.9 2450.68   561.9 2451.91   574.1 2455.63   590.3 2463.07     600 2468.52
#Mann= 5 ,-1,0
       0      .1       0     240     .12       0   279.8    .045       0
   315.2     .12       0     440      .1       0
Bank Sta=279.8,315.2
XS Rating Curve= 0 ,0
Exp/Cntr(USF)=0,0
Exp/Cntr=0.3,0.1

Type RM Length L Ch R = 1 ,18122   ,359.4,352,344.1
XS GIS Cut Line= 2
2271132.10853946411824.7713122662270546.03615693411925.127386264
#Sta/Elev= 30
       0 2526.59       8 2523.79    16.2 2519.44    20.2 2518.06    28.3 2517.76
    32.4 2516.27    40.5 2512.07    77.8 2497.34    93.3 2489.68   100.8 2485.22
   113.6 2476.92   116.9 2473.41   125.7 2459.24   129.8 2453.36   137.9 2443.16
   141.22440.326     142 2439.64     146 2438.62   150.1  2438.6   154.1 2438.62
   166.3 2440.37   186.6 2444.46   206.9 2445.63   373.3 2448.58   417.9 2448.25
   489.1 2449.02   543.7 2450.38   555.9 2451.33   575.5 2456.24   594.6 2466.13
#Mann= 7 ,-1,0
       0      .1       0     130     .12       0   141.2    .045       0
   166.3     .12       0     230      .1       0     330     .12       0
     430      .1       0
Bank Sta=141.2,166.3
XS Rating Curve= 0 ,0
Exp/Cntr(USF)=0,0
Exp/Cntr=0.3,0.1

Type RM Length L Ch R = 1 ,17770   ,438.8,433.6,423.5
XS GIS Cut Line= 5
2270968.42834482411457.7528605632270840.75116377411539.935178163
2270715.49311071411650.9747495272270593.62041043411704.463323538
2270465.66885009411785.217195202
#Sta/Elev= 30
       0 2454.59     6.3 2450.04    13.7 2445.54      20 2443.44    71.7 2442.62
      75  2442.2    81.2 2440.5294.198622438.505   100.2 2437.69   119.2  2437.9
124.39822438.388     130 2439.05   138.7 2441.86     143 2442.14     190 2440.69
     202 2441.07   222.1 2440.72   254.2 2441.34   280.9 2441.29   316.5  2442.8
   344.6 2444.69   375.3 2445.51   404.3  2447.5   427.7 2448.45   482.4  2453.1
   534.4 2455.94   548.6 2458.24   564.1 2458.77     577 2460.88   603.6 2462.74
#Mann= 4 ,-1,0
       0     .12       094.19862    .045       0124.3982     .12       0
  319.23      .1       0
#XS Ineff= 1 ,-1
  145.69     600 2444.04
Permanent Ineff=
       F
Bank Sta=94.19862,124.3982
XS Rating Curve= 0 ,0
Exp/Cntr(USF)=0,0
Exp/Cntr=0.3,0.1

Type RM Length L Ch R = 1 ,17336   ,216.5,231.2,244.8
BEGIN DESCRIPTION:
structure xs 4
END DESCRIPTION:
XS GIS Cut Line= 4
2270763.05212765411246.6268016552270649.14019611411287.387860366
2270479.91739589 411427.902580922270328.16936952411638.505444986
#Sta/Elev= 30
       0 2442.02    29.3 2441.69    41.3 2440.72    85.6 2440.75   167.6 2438.01
   179.4 2438.81   191.1 2438.24   225.2 2438.13   242.8 2438.74     265 2438.26
   273.5 2437.09   286.6 2436.36   311.6 2437.57   333.1 2436.45344.62052435.159
     361 2433.88   367.9 2434.02373.32042435.115   378.9 2437.87   386.9 2440.68
   390.4 2441.33   430.5 2444.34   450.6 2444.61   490.4 2447.06   511.6 2450.16
   518.4 2451.64   527.9 2454.71   538.9 2455.83   559.4    2468   600.5 2489.58
#Mann= 6 ,-1,0
       0     .12       0  160.99     .08       0  200.99     .12       0
344.6205    .045       0373.3204     .12       0  440.94      .1       0
#XS Ineff= 2 , 0
          243.36 2440.77
Permanent Ineff=
       F       F
Bank Sta=344.6205,373.3204
XS Rating Curve= 0 ,0
Exp/Cntr(USF)=0,0
Exp/Cntr=0.5,0.3

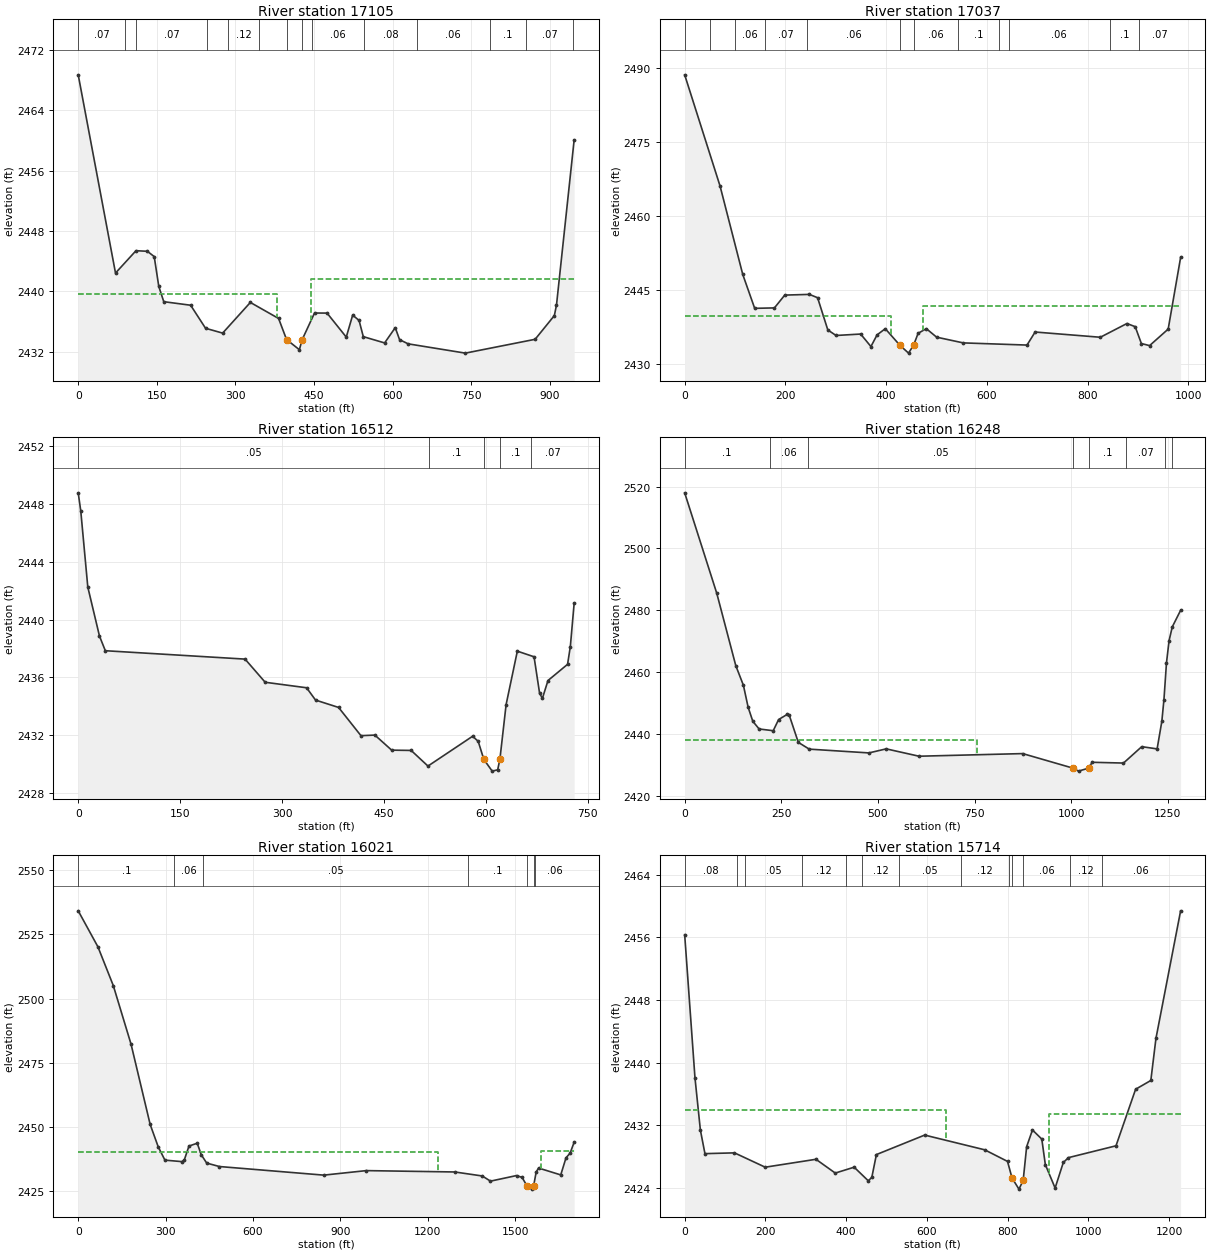
Type RM Length L Ch R = 1 ,17105   ,68.9,68.5,68.5
BEGIN DESCRIPTION:
structure xs 3; 17.6 ft between structure and xs
END DESCRIPTION:
XS GIS Cut Line= 5
2270660.69254404 411059.590470082270595.94801235 411212.49776832
2270085.31580025411307.5789384432269912.85674927411352.911978335
2269896.90810191411434.329032155
#Sta/Elev= 30
       0 2468.68    71.2 2442.44   110.3  2445.4     132 2445.32   145.1 2444.62
   153.8 2440.67   163.3 2438.65   214.6 2438.18   243.1 2435.13   275.7 2434.49
   328.6 2438.55   382.5 2436.43   397.7 2433.64   422.2 2432.29   427.32433.591
   451.1 2437.15     475 2437.14   511.7 2433.96   523.9 2436.87   536.1 2436.17
   544.2 2434.02   584.9 2433.19   605.2 2435.21   613.4 2433.63   629.7 2433.07
     739 2431.84   872.2 2433.67   908.9 2436.81     913 2438.21   946.7 2460.07
#Mann= 14 ,-1,0
       0     .07       0      90     .08       0     110     .07       0
  246.05     .06       0  286.05     .12       0  346.05      .1       0
   397.7    .045       0   427.3      .1       0  446.05     .06       0
  546.05     .08       0  646.05     .06       0  785.46      .1       0
  855.46     .07       0  943.78      .1       0
#XS Ineff= 2 , 0
             380  2439.7     444          2441.7
Permanent Ineff=
       F       F
Bank Sta=397.7,427.3
XS Rating Curve= 0 ,0
Exp/Cntr(USF)=0,0
Exp/Cntr=0.5,0.3

Type RM Length L Ch R = 1 ,17037   ,540.8,524.4,485.2
BEGIN DESCRIPTION:
structure xs 2; 18.4 ft between structure and xs
END DESCRIPTION:
XS GIS Cut Line= 5
2270661.38131565410994.8459383932270581.21911703411148.346223822
2270089.92900643411243.3967065122269917.40230209411292.683386187
2269888.96533869411421.326792036
#Sta/Elev= 30
       0 2488.53    70.3 2466.01   115.3 2448.15     139 2441.29   178.2 2441.38
   198.7 2443.97   247.6 2444.11   263.9 2443.44   284.2 2436.92   300.5  2435.8
   349.4 2436.09   369.8 2433.56     382 2435.92   398.3 2437.17   427.4 2433.81
   444.5 2432.23   454.7 2433.89   463.5 2436.24   479.8 2437.18   500.2 2435.46
   553.1  2434.3   679.7 2433.86   695.8  2436.5   825.3 2435.44   878.1 2438.22
   894.5 2437.58   906.8 2434.17   923.1 2433.75     960 2437.09   984.7 2451.59
#Mann= 12 ,-1,0
       0     .12       0      50     .07       0     100     .06       0
     160     .07       0  243.17     .06       0   427.4    .045       0
   454.7     .06       0  543.17      .1       0  623.17     .08       0
  643.17     .06       0  843.57      .1       0     903     .07       0
#XS Ineff= 2 , 0
             409  2439.7     473          2441.7
Permanent Ineff=
       F       F
Bank Sta=427.4,454.7
XS Rating Curve= 0 ,0
Exp/Cntr(USF)=0,0
Exp/Cntr=0.5,0.3

Type RM Length L Ch R = 1 ,16512   ,269.4,264.4,247.2
BEGIN DESCRIPTION:
structure xs 1
END DESCRIPTION:
XS GIS Cut Line= 3
2270004.85771122410750.1156367222269796.61392954411038.482224914
2269881.94839805411402.660326886
#Sta/Elev= 30
       0 2448.76     3.8 2447.49    14.1 2442.25    31.3 2438.86    39.9 2437.85
   245.5 2437.27   275.1 2435.67     336 2435.29   349.2 2434.44   383.1 2433.93
     416 2431.98   436.5 2432.02   461.2 2430.98   489.9 2430.96   514.6 2429.88
   580.3 2431.94   588.5 2431.59   596.8 2430.34   609.1 2429.53   617.2 2429.62
   620.5 2430.37   629.6 2434.13   646.1 2437.82   670.7 2437.43   678.9  2434.9
     683 2434.56   691.2 2435.79     720 2436.91   724.1 2438.14   729.7 2441.13
#Mann= 5 ,-1,0
       0     .05       0   515.7      .1       0   596.8    .045       0
   620.5      .1       0   665.7     .07       0
Bank Sta=596.8,620.5
XS Rating Curve= 0 ,0
Exp/Cntr(USF)=0,0
Exp/Cntr=0.3,0.1

Type RM Length L Ch R = 1 ,16248   ,231.2,226.2,216.1
XS GIS Cut Line= 3
2269731.25941278410235.4421976342269579.19181097411114.323187731
2269745.83227599411468.194135544
#Sta/Elev= 30
       0 2517.99      83 2485.51   132.2 2462.12     152 2455.72   164.1 2448.68
   176.3  2444.1   192.6 2441.62   229.1 2441.06     243 2444.67   265.6 2446.37
   270.6 2446.05     294 2437.29   322.3  2435.1   476.7 2433.88   521.4 2435.19
   606.3 2432.81   874.5 2433.66  1005.6 2428.92  1018.9 2427.99  1045.1 2428.96
  1054.3 2430.85  1135.3  2430.6  1182.5  2435.9  1222.3 2435.18  1234.5 2444.09
    1240 2451.15  1246.5 2462.97  1253.2 2470.17  1261.5 2474.63  1283.1    2480
#Mann= 8 ,-1,0
       0      .1       0     220     .06       0     320     .05       0
  1005.6    .045       0  1045.1      .1       0 1141.94     .07       0
 1241.94     .06       0 1261.94     .07       0
#XS Ineff= 2 , 0
          757.18  2437.9
Permanent Ineff=
       F       F
Bank Sta=1005.6,1045.1
XS Rating Curve= 0 ,0
Exp/Cntr(USF)=0,0
Exp/Cntr=0.3,0.1

Type RM Length L Ch R = 1 ,16021   ,306.2,307.2,306.5
XS GIS Cut Line= 3
2269601.30632387409930.4514169082269386.37127014411180.311525661
2269615.89099656 411548.86899982
#Sta/Elev= 30
       0 2534.18    67.7 2520.15   120.5 2505.04   181.4 2482.23     247 2450.98
   274.7 2442.25   297.7 2437.09   355.9 2436.51     364 2437.13   380.2 2442.57
   408.5 2443.68   422.4 2439.18   441.1 2435.94   484.7  2434.6   842.9 2431.25
     989 2433.01  1292.8 2432.48    1387 2430.92  1415.2 2428.91  1504.8 2431.09
  1523.7 2430.35  1540.2 2427.12  1556.7  2425.8  1563.4 2427.16  1572.1 2432.48
  1580.2 2434.01  1656.4 2431.34  1674.5 2438.01  1688.6 2439.83  1702.4 2444.08
#Mann= 7 ,-1,0
       0      .1       0     330     .06       0     430     .05       0
 1338.21      .1       0  1540.2    .045       0  1563.4     .07       0
 1568.21     .06       0
#XS Ineff= 2 , 0
         1236.17 2440.44 1590.08          2440.7
Permanent Ineff=
       F       F
Bank Sta=1540.2,1563.4
XS Rating Curve= 0 ,0
Exp/Cntr(USF)=0,0
Exp/Cntr=0.3,0.1

Type RM Length L Ch R = 1 ,15714   ,353.2,353.9,354.3
XS GIS Cut Line= 4
2268753.37861125410940.9838670772269177.96488342411331.566462916
2269175.26486719411388.266803929 2269489.9094147411893.037150296
#Sta/Elev= 30
       0 2456.32    25.5 2438.05    38.9 2431.38    50.2 2428.37   123.4 2428.47
   199.5 2426.64   325.2 2427.65     373 2425.89   419.8 2426.64   454.9  2424.9
   463.6 2425.35   474.9 2428.25   594.5 2430.74   743.2 2428.86   799.7 2427.38
810.87472425.263     828 2423.84838.47452424.943   847.1 2429.26   861.5 2431.39
   884.6 2430.23   893.4 2426.97   917.6 2423.98   937.9 2427.24   950.6 2427.86
  1068.4 2429.37    1117 2436.59  1154.7 2437.71  1167.4 2443.08  1228.5 2459.37
#Mann= 13 ,-1,0
       0     .08       0     130     .07       0     150     .05       0
     290     .12       0     400      .1       0     440     .12       0
     530     .05       0  683.68     .12       0  803.68     .06       0
810.8747    .045       0838.4745     .06       0  953.68     .12       0
 1033.68     .06       0
#XS Ineff= 2 , 0
          646.76 2433.97   903.1         2433.48
Permanent Ineff=
       F       F
Bank Sta=810.8747,838.4745
XS Rating Curve= 0 ,0
Exp/Cntr(USF)=0,0
Exp/Cntr=0.3,0.1

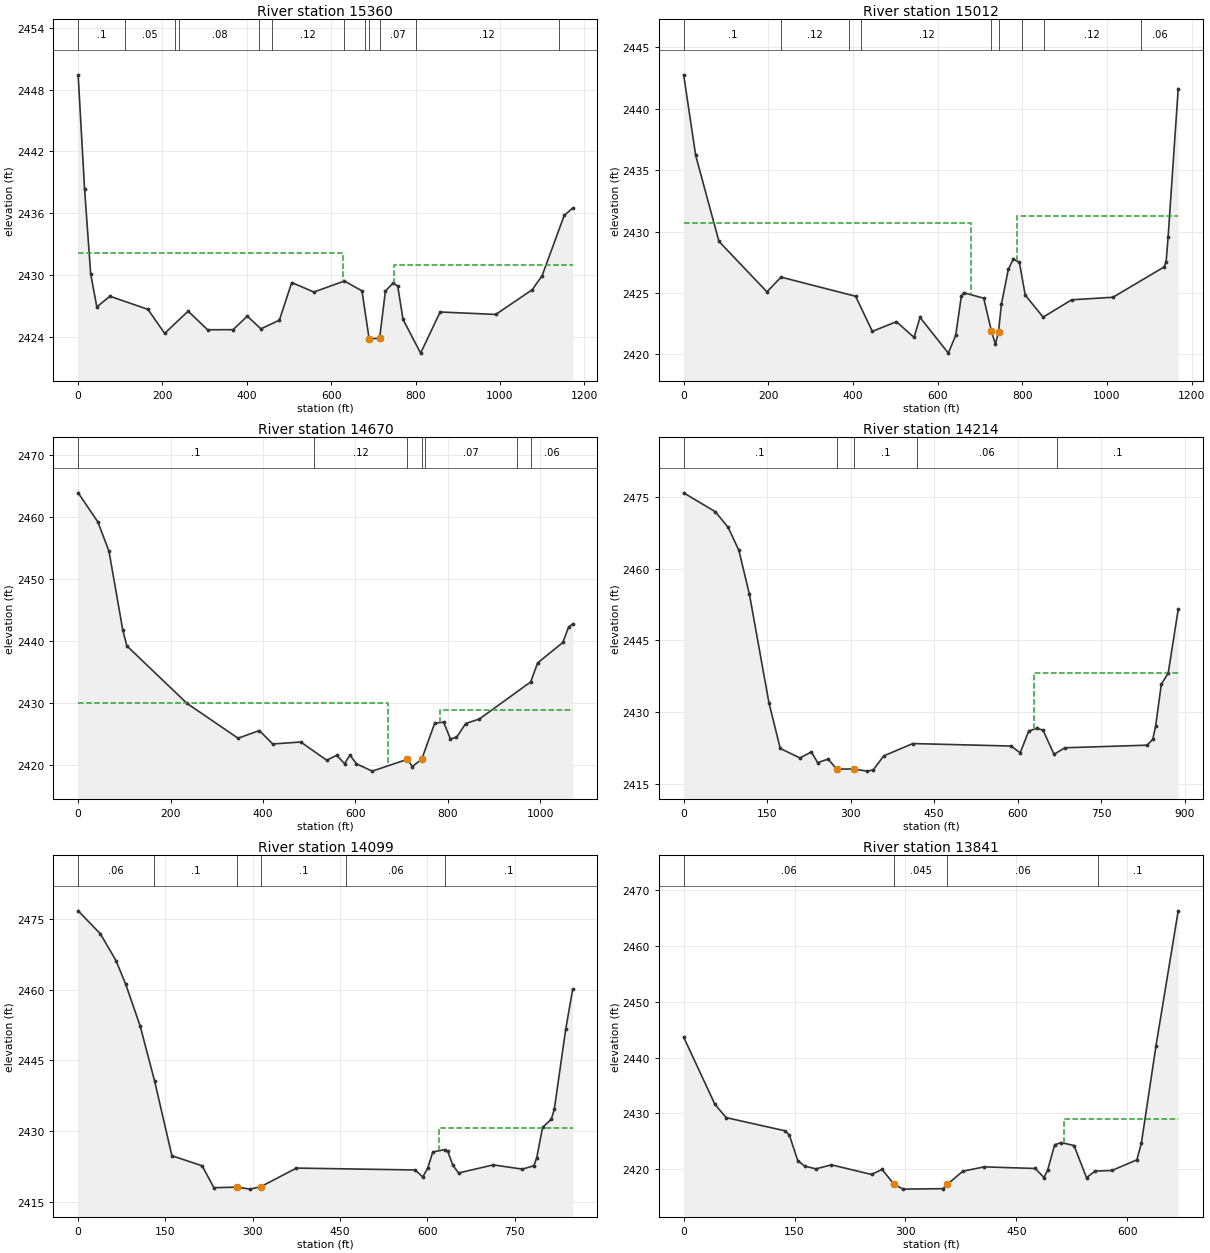
Type RM Length L Ch R = 1 ,15360   ,346.7,348.2,346.3
XS GIS Cut Line= 2
2268632.60072203411140.0867103182269224.19122432412152.479349119
#Sta/Elev= 30
       0 2449.44    15.2 2438.37    29.7  2430.1    44.3 2426.88    75.4 2427.92
   165.6 2426.64   205.1 2424.31   260.8 2426.47     307 2424.66   367.3 2424.67
   401.1 2425.99   433.3 2424.75   477.1 2425.59   506.4 2429.25     559 2428.33
   631.3  2429.4     673 2428.44689.89532423.801   714.7 2423.82   728.6 2428.44
   747.2 2429.21   757.8  2428.9   770.3 2425.67     812 2422.39   858.3 2426.39
   990.2 2426.15  1076.6 2428.55    1100 2429.91  1152.6 2435.78  1172.6 2436.49
#Mann= 12 ,-1,0
       0      .1       0     110     .05       0     230     .12       0
     240     .08       0     430      .1       0     460     .12       0
     630      .1       0     680     .07       0689.8953    .045       0
   714.7     .07       0     800     .12       0    1140     .06       0
#XS Ineff= 2 , 0
          627.38 2432.15  749.07         2430.91
Permanent Ineff=
       F       F
Bank Sta=689.8953,714.7
XS Rating Curve= 0 ,0
Exp/Cntr(USF)=0,0
Exp/Cntr=0.3,0.1

Type RM Length L Ch R = 1 ,15012   ,342.9,342,341.5
XS GIS Cut Line= 2
2268333.91278596411296.9737144032268943.57594836412293.504891805
#Sta/Elev= 30
       0 2442.77    28.4 2436.21    83.3 2429.21   196.7  2425.1     230  2426.3
   406.2 2424.74   445.7 2421.88   502.5 2422.67   544.2 2421.39   558.3 2423.02
   625.2 2420.11   642.7 2421.57   655.8 2424.73   661.4 2425.03   708.8 2424.58
   727.1 2421.89   736.4 2420.84   743.7 2421.85   750.5 2424.08   766.8 2426.92
   778.6 2427.78   793.1 2427.49   806.8 2424.84     849 2423.04   916.4 2424.45
  1014.2 2424.66    1135 2427.13  1139.7 2427.57  1144.4  2429.6  1168.2 2441.64
#Mann= 9 ,-1,0
       0      .1       0     230     .12       0     390      .1       0
     420     .12       0   727.1    .045       0   743.7     .12       0
     800     .06       0     850     .12       0    1080     .06       0
#XS Ineff= 2 , 0
          678.08 2430.67  787.61          2431.3
Permanent Ineff=
       F       F
Bank Sta=727.1,743.7
XS Rating Curve= 0 ,0
Exp/Cntr(USF)=0,0
Exp/Cntr=0.3,0.1

Type RM Length L Ch R = 1 ,14670   ,444.9,456.2,460.8
XS GIS Cut Line= 2
2268022.82316628411505.9293153142268622.28051008412392.510240385
#Sta/Elev= 30
       0 2463.85    42.6 2459.18    66.7 2454.47    96.5 2441.82   105.3 2439.24
   235.7 2429.98   346.1 2424.38   392.2 2425.62     421 2423.46   481.9 2423.77
     538 2420.84   559.4 2421.63   576.6  2420.3   588.2 2421.68   602.3 2420.26
   636.5 2419.09     712 2420.98   723.4 2419.83743.60592421.027   771.7 2426.82
     791 2426.96   805.5 2424.29   818.6  2424.5   838.7 2426.75   868.2 2427.47
   979.3 2433.44   994.3 2436.49    1049 2439.79  1061.4 2442.29  1070.2 2442.76
#Mann= 7 ,-1,0
       0      .1       0     510     .12       0     712    .045       0
743.6059     .12       0     750     .07       0     950     .12       0
     980     .06       0
#XS Ineff= 2 , 0
          669.97 2429.98   782.2         2428.93
Permanent Ineff=
       F       F
Bank Sta=712,743.6059
XS Rating Curve= 0 ,0
Exp/Cntr(USF)=0,0
Exp/Cntr=0.3,0.1

Type RM Length L Ch R = 1 ,14214   ,113.9,114.5,111.1
XS GIS Cut Line= 2
2267867.19063535411792.3048400472268413.32795558 412493.16019221
#Sta/Elev= 30
       0 2475.81    56.9 2471.86    79.7 2468.64    99.2  2463.8   118.2 2454.59
   153.2 2431.97   173.5 2422.42     209 2420.43   229.4 2421.69   240.7 2419.46
   259.7 2420.19   274.9 2418.09   305.4 2418.14   329.1 2417.68   340.5 2417.92
   359.5 2420.87   411.7 2423.44   588.4 2422.92   604.6  2421.5   619.8 2426.03
     634 2426.62   645.5 2426.26   665.4 2421.19   684.9 2422.56   832.8  2423.1
   842.9 2424.36     848 2427.14   858.1 2435.79   870.6 2438.21   888.5 2451.46
#Mann= 5 ,-1,0
       0      .1       0   274.9    .045       0   305.4      .1       0
     420     .06       0     670      .1       0
#XS Ineff= 2 , 0
                           629.3         2438.28
Permanent Ineff=
       F       F
Bank Sta=274.9,305.4
XS Rating Curve= 0 ,0
Exp/Cntr(USF)=0,0
Exp/Cntr=0.3,0.1

Type RM Length L Ch R = 1 ,14099   ,257.3,258.5,271
XS GIS Cut Line= 2
2267789.53381975411855.6435802052268294.81537205412538.845458502
#Sta/Elev= 30
       0 2476.78    38.1 2471.91      65 2466.22    81.5 2461.26   106.4 2452.37
   131.3 2440.66   161.1 2424.75     213 2422.62   233.2 2417.97   273.5 2418.08
   295.4 2417.66   313.9 2418.18     375 2422.13     579 2421.73   592.1 2420.24
   600.7 2422.14   609.3 2425.55     630 2426.05     635 2425.69   643.7 2422.76
   653.6 2421.09   713.3 2422.81   763.1 2421.91     783 2422.62     788 2424.36
   797.9 2430.78   812.9 2432.51   818.1 2434.62   837.7 2451.62   849.7 2460.12
#Mann= 6 ,-1,0
       0     .06       0     130      .1       0   273.5    .045       0
   313.9      .1       0     460     .06       0     630      .1       0
#XS Ineff= 2 , 0
                          619.15         2430.63
Permanent Ineff=
       F       F
Bank Sta=273.5,313.9
XS Rating Curve= 0 ,0
Exp/Cntr(USF)=0,0
Exp/Cntr=0.3,0.1

Type RM Length L Ch R = 1 ,13841   ,273.1,275.5,275.2
XS GIS Cut Line= 2
2267657.19855525412075.7183886672268066.39379368412604.898828048
#Sta/Elev= 30
       0 2443.64    42.3 2431.63    57.5 2429.26   137.2  2426.9   142.9 2426.16
   154.3 2421.58   163.7  2420.6   178.8  2420.1   199.9 2420.82   254.1  2419.1
   268.3    2420284.77812417.324   296.9 2416.48   350.7 2416.56356.37252417.314
   377.6 2419.68   406.4 2420.46   475.7 2420.17   487.3 2418.54   492.3 2419.88
   501.8  2424.4   510.7  2424.8     528 2424.27   544.9 2418.52   556.3  2419.7
   579.2 2419.81     613 2421.71   619.1 2424.71   638.9 2442.14   668.9 2466.22
#Mann= 4 ,-1,0
       0     .06       0284.7781    .045       0356.3725     .06       0
     560      .1       0
#XS Ineff= 2 , 0
                          514.25            2429
Permanent Ineff=
       F       F
Bank Sta=284.7781,356.3725
XS Rating Curve= 0 ,0
Exp/Cntr(USF)=0,0
Exp/Cntr=0.3,0.1

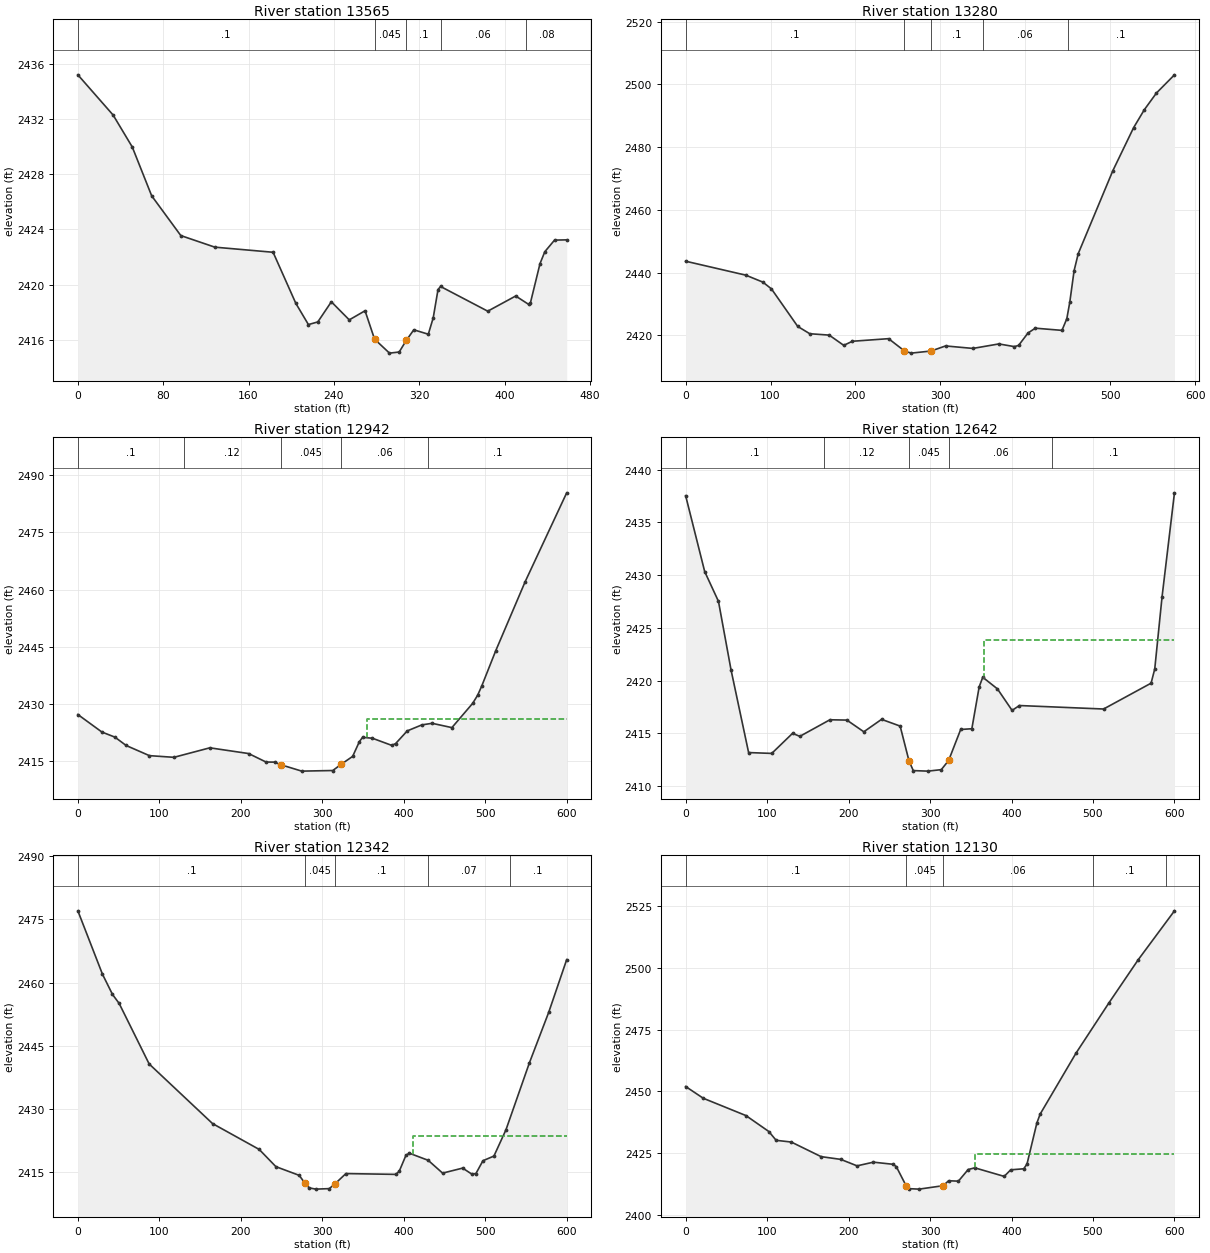
Type RM Length L Ch R = 1 ,13565   ,287.2,285.4,281.7
XS GIS Cut Line= 2
 2267508.1495718412244.3131900352267726.44472419412647.202333559
#Sta/Elev= 30
       0  2435.2    33.1 2432.28      51 2429.97    69.2 2426.43    96.5 2423.55
   128.4 2422.71     183 2422.34   204.3 2418.64   216.1  2417.1   224.9 2417.29
   237.6 2418.75   254.4 2417.44   269.2  2418.1 278.0992416.044   292.1 2415.03
   301.2 2415.11307.79892415.947   314.9 2416.72   328.5  2416.4   333.1 2417.59
   337.6 2419.64     340 2419.86   384.2 2418.07   410.4 2419.17   422.6 2418.56
   424.1 2418.64   433.2 2421.52   437.7 2422.38   446.8 2423.22   458.2 2423.24
#Mann= 5 ,-1,0
       0      .1       0 278.099    .045       0307.7989      .1       0
     340     .06       0     420     .08       0
Bank Sta=278.099,307.7989
XS Rating Curve= 0 ,0
Exp/Cntr(USF)=0,0
Exp/Cntr=0.3,0.1

Type RM Length L Ch R = 1 ,13280   ,341.9,338,333.4
XS GIS Cut Line= 2
2267259.84161927412452.6362537752267607.53609321412911.470294376
#Sta/Elev= 30
       0 2443.67    70.9 2439.22      91    2437   101.1 2434.84     132 2422.89
   146.2 2420.56   169.1 2420.12   186.2 2416.86   196.4 2418.16     239 2418.99
   257.6  2415.1   265.5 2414.38     289 2415.05   306.1 2416.67   338.3 2415.88
   368.9 2417.31   387.1 2416.46   392.1 2416.83   403.2 2420.79   411.8 2422.33
   443.2 2421.63   448.9 2425.32   452.4 2430.58   457.5 2440.66   462.4 2446.11
   503.1  2472.5   527.6 2486.23   540.2 2491.94   554.5 2497.27   575.7 2503.06
#Mann= 5 ,-1,0
       0      .1       0   257.6    .045       0     289      .1       0
     350     .06       0     450      .1       0
Bank Sta=257.6,289
XS Rating Curve= 0 ,0
Exp/Cntr(USF)=0,0
Exp/Cntr=0.3,0.1

Type RM Length L Ch R = 1 ,12942   ,306.6,300,293
XS GIS Cut Line= 2
2266981.95497215412727.7520056762267434.54441133413121.659100748
#Sta/Elev= 30
       0 2427.25    29.5 2422.66    45.4 2421.33    59.3 2419.13    87.8 2416.47
   117.9 2416.03     162 2418.52   209.6 2417.02     231 2414.79   241.6 2414.77
   249.2 2414.08   274.8 2412.41   312.9 2412.57     323 2414.17   337.3 2416.28
   345.6 2420.17   349.5 2421.27   361.6 2421.03   385.3 2419.16     390 2419.63
   404.3 2422.96   422.2 2424.53   434.8 2424.95   459.1 2423.82   484.6 2430.18
   490.8 2432.35   495.7 2434.71   512.9 2443.97   549.1 2462.11     600 2485.38
#Mann= 5 ,-1,0
       0      .1       0     130     .12       0   249.2    .045       0
     323     .06       0     430      .1       0
#XS Ineff= 2 , 0
                          354.91         2426.08
Permanent Ineff=
       F       F
Bank Sta=249.2,323
XS Rating Curve= 0 ,0
Exp/Cntr(USF)=0,0
Exp/Cntr=0.3,0.1

Type RM Length L Ch R = 1 ,12642   ,306.2,300,295.1
XS GIS Cut Line= 2
2266731.33029804412999.7911796362267265.69727393413272.649998592
#Sta/Elev= 30
       0 2437.54    23.4 2430.34    40.3 2427.52    55.8 2420.99    77.3 2413.18
   105.7  2413.1   131.2    2415   140.2 2414.72   177.1 2416.29   197.9 2416.26
   218.7 2415.15   240.5 2416.33   263.3 2415.69   274.1 2412.41   279.4 2411.47
   297.4 2411.42   313.8 2411.56   322.8 2412.43   337.6 2415.37   351.3 2415.44
   360.3 2419.41   364.7 2420.32   382.7 2419.22   400.7 2417.18   409.7 2417.64
     513 2417.31   571.3 2419.76   575.8 2421.11   584.8 2427.97     600 2437.81
#Mann= 5 ,-1,0
       0      .1       0     170     .12       0   274.1    .045       0
   322.8     .06       0     450      .1       0
#XS Ineff= 2 , 0
                          366.76         2423.89
Permanent Ineff=
       F       F
Bank Sta=274.1,322.8
XS Rating Curve= 0 ,0
Exp/Cntr(USF)=0,0
Exp/Cntr=0.3,0.1

Type RM Length L Ch R = 1 ,12342   ,219.6,211.9,206.8
XS GIS Cut Line= 2
2266558.62703999413331.419704541 2267145.0059279413458.540905815
#Sta/Elev= 30
       0 2477.05    30.2 2462.01    42.5 2457.21    50.7 2455.07    87.5 2440.71
   165.3 2426.56   222.6 2420.42   243.1 2416.33   271.7 2414.27   278.6 2412.44
     284 2411.29   292.1    2411   308.6 2411.12   315.6 2412.26     329 2414.69
   390.4  2414.5   394.5 2415.26   402.7 2419.02   406.8 2419.53     430 2417.84
   447.7  2414.8   472.3 2415.99   483.8 2414.53   488.6  2414.7   497.2 2417.74
   510.7 2418.85   525.5  2425.1   554.1  2440.9     578    2453     600 2465.47
#Mann= 5 ,-1,0
       0      .1       0   278.6    .045       0   315.6      .1       0
     430     .07       0     530      .1       0
#XS Ineff= 2 , 0
                          411.38         2423.68
Permanent Ineff=
       F       F
Bank Sta=278.6,315.6
XS Rating Curve= 0 ,0
Exp/Cntr(USF)=0,0
Exp/Cntr=0.3,0.1

Type RM Length L Ch R = 1 ,12130   ,407.3,393,377.3
XS GIS Cut Line= 2
 2266586.3708398413626.6837424172267184.60198082413580.645693899
#Sta/Elev= 30
       0 2451.98    21.7 2447.21      74 2440.21   102.1 2433.75   111.1 2430.18
   129.7 2429.48   166.3 2423.57   190.4 2422.46   210.4 2419.84   230.5 2421.33
   254.6 2420.47   258.6 2419.51   270.6 2411.79   274.6 2410.59   286.6 2410.41
     316  2411.8   322.8  2413.8   334.8 2413.64   346.8 2418.35   354.9 2419.04
     391 2415.57     399 2418.23     415 2418.65     419 2420.57   431.1 2437.19
   435.1 2440.78   479.2 2465.52   519.3 2485.72   555.4 2503.28     600 2523.14
#Mann= 5 ,-1,0
       0      .1       0   270.6    .045       0     316     .06       0
     500      .1       0     590     .12       0
#XS Ineff= 2 , 0
                          355.61         2424.45
Permanent Ineff=
       F       F
Bank Sta=270.6,316
XS Rating Curve= 0 ,0
Exp/Cntr(USF)=0,0
Exp/Cntr=0.3,0.1

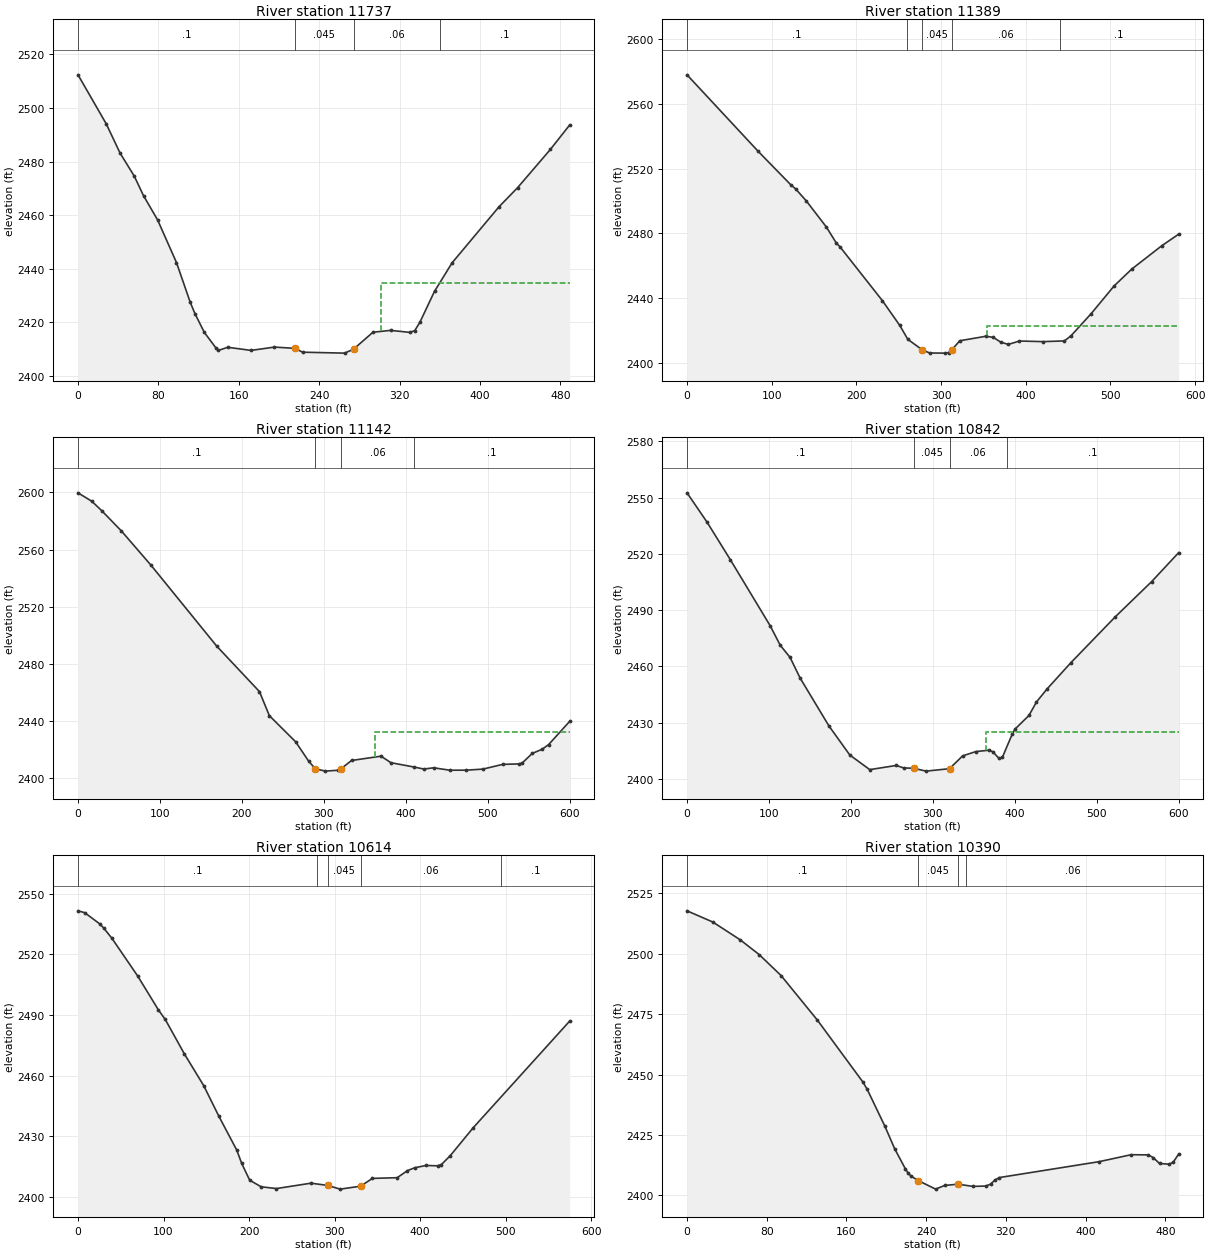
Type RM Length L Ch R = 1 ,11737   ,340.2,348.1,349.1
XS GIS Cut Line= 2
2266768.12125542414095.3853319812267188.69197416413845.423489711
#Sta/Elev= 30
       0 2512.38      28 2494.16    41.9 2483.15    55.9 2474.64    65.2 2467.28
    79.2 2458.24      98 2442.32   111.7 2427.47   116.4 2423.24   125.7 2416.25
   137.4 2410.39   139.7 2409.53     149  2410.7   172.2 2409.54   195.5 2410.77
   215.7 2410.31   223.5 2408.87   265.3 2408.52   274.2    2410   293.5 2416.32
     311 2417.01   330.4 2416.26   335.1 2416.94   340.2 2420.04   354.8 2431.62
   372.3 2442.25   418.8 2463.08   437.5  2470.3     470 2484.52   489.2 2493.64
#Mann= 4 ,-1,0
       0      .1       0   215.7    .045       0   274.2     .06       0
     360      .1       0
#XS Ineff= 2 , 0
                           301.5         2434.54
Permanent Ineff=
       F       F
Bank Sta=215.7,274.2
XS Rating Curve= 0 ,0
Exp/Cntr(USF)=0,0
Exp/Cntr=0.3,0.1

Type RM Length L Ch R = 1 ,11389   ,240.2,247,255.9
XS GIS Cut Line= 2
 2266844.5366295414372.2003633712267370.41654934414126.214033548
#Sta/Elev= 30
       0 2577.97    84.2 2530.56   122.3 2510.09   128.4 2507.35   140.9 2499.96
   164.5 2483.89   176.2 2474.03   180.7 2471.55   230.7 2438.31   251.3 2422.95
   260.7 2414.41   277.8 2407.85   286.6 2405.93   304.3 2405.84   308.9 2406.19
   313.1 2408.05     322 2413.48   352.9 2416.27   361.7  2415.6   370.5 2412.64
   379.4 2411.23   392.6 2413.34   420.2 2412.95   445.6 2413.39   453.3 2416.46
   477.4 2430.33   504.4 2447.42   525.1 2457.77   560.4 2472.16   580.6 2479.41
#Mann= 5 ,-1,0
       0      .1       0     260     .06       0   277.8    .045       0
   313.1     .06       0     440      .1       0
#XS Ineff= 2 , 0
                          353.92         2422.79
Permanent Ineff=
       F       F
Bank Sta=277.8,313.1
XS Rating Curve= 0 ,0
Exp/Cntr(USF)=0,0
Exp/Cntr=0.3,0.1

Type RM Length L Ch R = 1 ,11142   ,294.2,300,305.8
XS GIS Cut Line= 2
2266871.31914777414508.4130660162267469.68665413 414464.18267681
#Sta/Elev= 30
       0 2599.64    16.9 2593.72    28.9 2587.19      53 2572.95    89.1 2549.03
   169.3 2492.46   221.5 2460.64   233.5 2443.86   265.6 2425.59   281.6 2411.94
   289.6 2406.77   301.7 2405.07   317.7 2405.69   321.3 2406.86   333.8 2412.51
   369.8 2415.53   381.9 2410.96     410 2407.95     422 2406.53     434 2407.39
   454.1  2405.7   474.1 2405.75   494.2 2406.48   518.3  2409.8   538.3 2410.12
   542.3 2410.85   554.4 2417.47   566.4 2420.33   574.4 2423.65     600 2439.84
#Mann= 4 ,-1,0
       0      .1       0   289.6    .045       0   321.3     .06       0
     410      .1       0
#XS Ineff= 2 , 0
                          362.37         2432.75
Permanent Ineff=
       F       F
Bank Sta=289.6,321.3
XS Rating Curve= 0 ,0
Exp/Cntr(USF)=0,0
Exp/Cntr=0.3,0.1

Type RM Length L Ch R = 1 ,10842   ,219.4,227.9,235.4
XS GIS Cut Line= 2
2266887.87666427414739.524003209 2267480.7254854414831.883492637
#Sta/Elev= 30
       0  2552.5    24.6 2536.78    52.9 2516.86   101.5 2481.67   113.7 2471.35
   125.8  2464.8   137.9 2453.93   173.3 2428.25   198.7 2412.82     223 2405.05
   255.3 2407.27   264.4 2405.96   276.5 2405.77   291.8 2404.25   320.4 2405.55
   336.3 2412.36   352.5 2414.67   368.7 2415.39     373 2414.64   380.8 2411.01
   384.9 2411.63     397 2424.08   400.5 2426.72   417.3  2433.9   426.5  2441.1
   439.5 2448.08   468.3 2461.94   522.5 2486.38   567.1 2505.24     600 2520.63
#Mann= 4 ,-1,0
       0      .1       0   276.5    .045       0   320.4     .06       0
     390      .1       0
#XS Ineff= 2 , 0
                          364.73         2424.98
Permanent Ineff=
       F       F
Bank Sta=276.5,320.4
XS Rating Curve= 0 ,0
Exp/Cntr(USF)=0,0
Exp/Cntr=0.3,0.1

Type RM Length L Ch R = 1 ,10614   ,224,224.4,225.2
XS GIS Cut Line= 3
2266833.18283928414854.6523591242267221.26642762415051.281377217
2267360.97651942415051.281377217
#Sta/Elev= 30
       0 2541.62     7.8 2540.71    25.8 2535.03    30.3 2532.96    39.8 2527.92
    69.6 2509.43    94.1 2492.47     102 2487.79   124.4  2470.7     147 2454.97
   164.8 2439.73   185.7 2422.96   191.4 2416.42   200.7 2408.14   214.1 2404.85
     232 2403.97   272.4 2406.64   291.9 2405.53   306.5 2403.69   330.52405.156
   344.1 2409.01   373.2 2409.36   385.1 2412.84   393.5 2414.27   406.9 2415.41
   420.4 2415.25   424.9 2415.89   435.1  2420.2     462 2434.09   574.8 2486.95
#Mann= 5 ,-1,0
       0      .1       0     280     .06       0   291.9    .045       0
   330.5     .06       0  495.05      .1       0
Bank Sta=291.9,330.5
XS Rating Curve= 0 ,0
Exp/Cntr(USF)=0,0
Exp/Cntr=0.3,0.1

Type RM Length L Ch R = 1 ,10390   ,130,130.5,134
XS GIS Cut Line= 3
2266737.45555415415038.3452576062267055.68409659415212.982872359
2267139.76887407415312.590993366
#Sta/Elev= 30
       0 2517.79    25.9 2513.15    53.3 2505.81    72.4 2499.68    94.4 2490.99
   130.8 2472.55   176.5  2446.9   180.9 2443.81   198.5 2428.67   208.4 2419.27
   219.1 2410.98   222.1 2409.06     225  2407.9   232.3 2406.04   249.5 2402.55
   258.6 2404.08   272.2 2404.59   286.9 2403.68   299.7 2403.83   304.6 2404.59
   308.8 2406.27   313.4 2407.34   413.4 2413.91   445.8 2416.81     463 2416.72
   467.9  2415.6   474.2 2413.17   483.7 2412.88   487.8 2413.63   493.4 2417.07
#Mann= 4 ,-1,0
       0      .1       0   232.3    .045       0   272.2      .1       0
     280     .06       0
Bank Sta=232.3,272.2
XS Rating Curve= 0 ,0
Exp/Cntr(USF)=0,0
Exp/Cntr=0.3,0.1