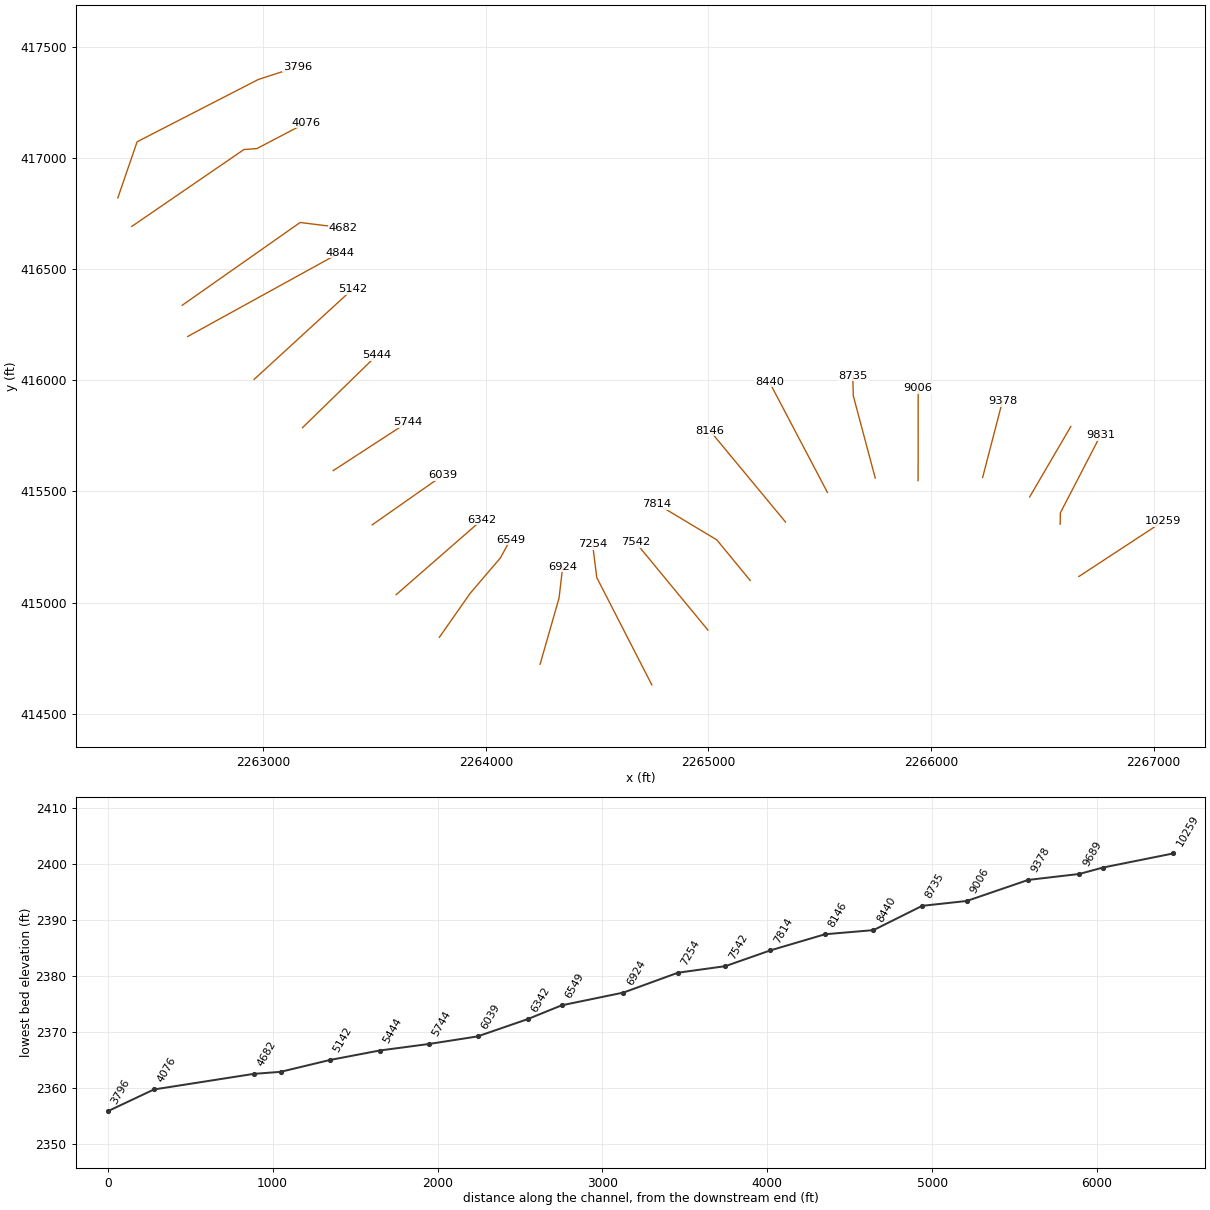
HEC-RAS study LAURELCK.prj: LAURELCK

--- LAURELCK.g01 (geometry) --- (continued)

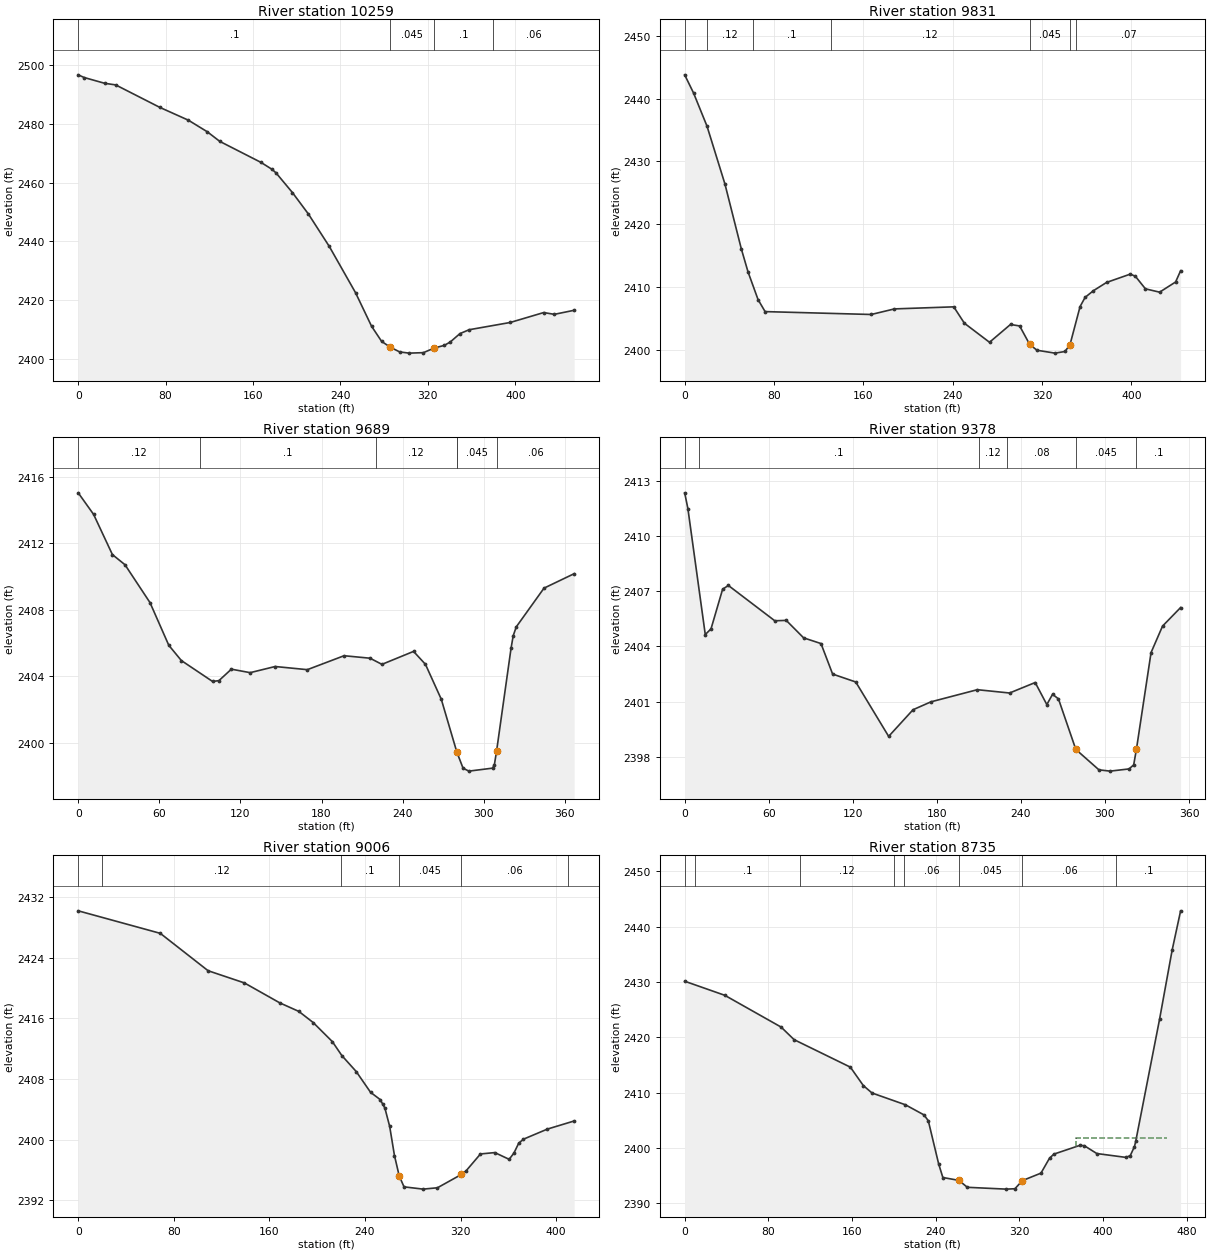
Type RM Length L Ch R = 1 ,10259   ,416.1,427.9,438.6
XS GIS Cut Line= 2
2266663.97368841415117.9244879392267043.57665375415366.860288841
#Sta/Elev= 30
       0 2496.65     5.4 2495.74    24.2 2493.77    34.3 2493.22    74.7 2485.57
   100.8 2481.22   118.1 2477.28   129.6    2474   167.2 2466.87   177.2 2464.54
     181 2463.31   196.1 2456.57   210.7 2449.28   229.8 2438.26   253.8 2422.53
   268.5  2411.1   277.7 2405.95   285.72403.957   294.3 2402.36   302.9 2401.96
   315.9 2402.12   325.92403.697   335.1  2404.6   340.5 2405.75   349.4 2408.61
   357.8 2409.92   395.4 2412.39     426 2415.76   435.8 2415.16   453.9 2416.54
#Mann= 4 ,-1,0
       0      .1       0   285.7    .045       0   325.9      .1       0
     380     .06       0
Bank Sta=285.7,325.9
XS Rating Curve= 0 ,0
Exp/Cntr(USF)=0,0
Exp/Cntr=0.3,0.1

Type RM Length L Ch R = 1 ,9831    ,143.5,142.2,140.5
XS GIS Cut Line= 3
2266580.04124562 415353.148329842266580.74871755 415403.87159719
2266761.52110462415753.134010348
#Sta/Elev= 30
       0  2443.8       8 2440.88      20 2435.61      36 2426.42    50.7 2416.06
    56.7 2412.39    65.7 2407.96      72 2406.05     167 2405.59   187.8 2406.48
   240.9 2406.81   250.4  2404.2   272.9 2401.16   291.7    2404   299.9 2403.76
   308.9 2400.81   315.4 2399.89   331.5 2399.43   340.5 2399.69     345  2400.8
     354 2406.86   358.5 2408.32   365.9 2409.38   377.7  2410.7     399 2412.03
   403.5 2411.68   412.5 2409.68   425.2 2409.15   439.5 2410.77     444 2412.57
#Mann= 7 ,-1,0
       0      .1       0      20     .12       0   60.73      .1       0
  130.73     .12       0   308.9    .045       0     345     .12       0
  350.73     .07       0
Bank Sta=308.9,345
XS Rating Curve= 0 ,0
Exp/Cntr(USF)=0,0
Exp/Cntr=0.3,0.1

Type RM Length L Ch R = 1 ,9689    ,304.3,311,317.4
XS GIS Cut Line= 2
2266442.72742582415475.2982162542266627.71236172415792.176042057
#Sta/Elev= 30
       0 2415.05    11.4 2413.75    25.3 2411.33    34.6 2410.72    53.1 2408.44
      67 2405.87    76.3 2404.95    99.4 2403.69   104.1 2403.74   113.3 2404.43
   127.2 2404.22   145.7 2404.59   169.5  2404.4   196.7 2405.24   215.9 2405.09
   224.7 2404.72   248.1  2405.5   256.9 2404.72   268.6 2402.62   280.1 2399.44
   284.7 2398.47     289 2398.29   306.6 2398.47   307.9 2398.68   309.5 2399.49
   320.2 2405.68   321.8 2406.44   324.1 2406.98   344.6 2409.31   366.9 2410.18
#Mann= 6 ,-1,0
       0     .12       0      90      .1       0     220     .12       0
     280     .06       0   280.1    .045       0   309.5     .06       0
Bank Sta=280.1,309.5
XS Rating Curve= 0 ,0
Exp/Cntr(USF)=0,0
Exp/Cntr=0.3,0.1

Type RM Length L Ch R = 1 ,9378    ,365,372.1,378
XS GIS Cut Line= 2
2266231.59613802415562.9840926942266320.53987329415905.593576247
#Sta/Elev= 30
       0 2412.36     2.3  2411.5    14.7 2404.65    18.8 2404.96    27.1 2407.12
    31.2 2407.32    64.3  2405.4    72.5 2405.42    84.9 2404.47    97.3 2404.16
   105.6  2402.5   122.1 2402.07   145.6 2399.11     163 2400.56   175.8 2400.99
   208.9 2401.65   231.9 2401.47   250.2 2402.04   258.5 2400.84   262.6  2401.4
   266.8 2401.15   279.2  2398.4   295.7 2397.29   303.7 2397.22   317.2 2397.34
   320.5 2397.56  322.492398.425   332.9 2403.67   341.1 2405.11     354 2406.12
#Mann= 6 ,-1,0
       0     .12       0      10      .1       0     210     .12       0
     230     .08       0   279.2    .045       0  322.49      .1       0
Bank Sta=279.2,322.49
XS Rating Curve= 0 ,0
Exp/Cntr(USF)=0,0
Exp/Cntr=0.3,0.1

Type RM Length L Ch R = 1 ,9006    ,259.1,270.6,277.4
XS GIS Cut Line= 2
2265941.69993247415548.4667684192265942.08336783415963.579116714
#Sta/Elev= 30
       0 2430.17    68.7  2427.2   108.7 2422.27   139.1 2420.66   168.7 2418.03
   184.7  2416.9   196.7 2415.43   212.7 2412.92   220.7 2411.07   232.7 2408.97
   244.7 2406.23   252.7 2405.28     255 2404.64   256.7 2404.14   260.7 2401.73
   264.7 2397.89268.69652395.192   272.7 2393.76   288.7 2393.46   300.7 2393.64
320.79582395.402   324.7 2395.88   336.7  2398.1   348.7 2398.28   360.7 2397.39
   364.7 2398.22   368.7 2399.52   372.7 2400.05   392.7 2401.38   415.1 2402.45
#Mann= 6 ,-1,0
       0      .1       0      20     .12       0     220      .1       0
268.6965    .045       0320.7958     .06       0     410      .1       0
Bank Sta=268.6965,320.7958
XS Rating Curve= 0 ,0
Exp/Cntr(USF)=0,0
Exp/Cntr=0.3,0.1

Type RM Length L Ch R = 1 ,8735    ,289.6,295.5,300.3
XS GIS Cut Line= 3
2265749.18873168415560.1122703192265650.55985657415929.979344437
2265648.22541306416021.259180874
#Sta/Elev= 30
       0 2430.16    38.4 2427.61    92.2 2421.87   104.6  2419.6   158.4 2414.63
   170.8  2411.3   179.1 2409.96   210.9 2407.84   228.8    2406   232.9 2404.94
   242.8 2397.14   246.8 2394.69262.19022394.168   270.2 2392.92   307.4 2392.59
   315.7 2392.66322.78782394.127   340.6 2395.48   348.8 2398.19     353 2398.92
   377.5 2400.48     382 2400.44     394 2399.02     422 2398.32     426 2398.66
     430 2400.29   431.2 2401.25     454 2423.31     466 2435.78   474.1 2442.88
#Mann= 8 ,-1,0
       0     .12       0      10      .1       0     110     .12       0
     200      .1       0     210     .06       0262.1902    .045       0
322.7878     .06       0  412.79      .1       0
#XS Ineff= 1 ,-1
   373.8     461 2401.74
Permanent Ineff=
       F
Bank Sta=262.1902,322.7878
XS Rating Curve= 0 ,0
Exp/Cntr(USF)=0,0
Exp/Cntr=0.3,0.1

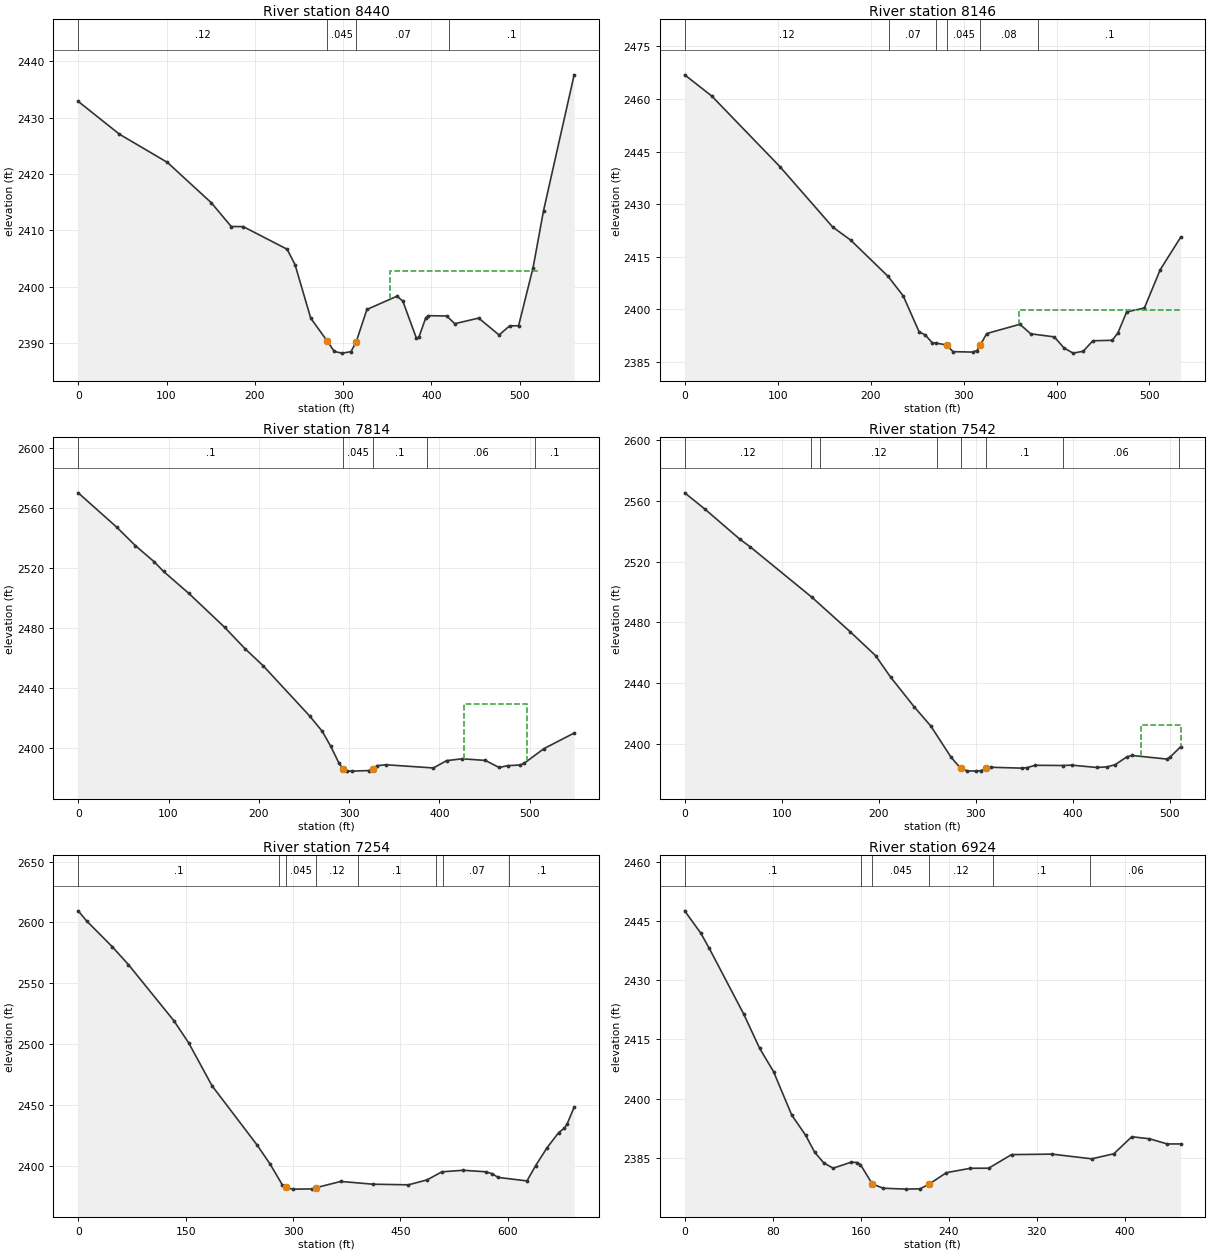
Type RM Length L Ch R = 1 ,8440    ,288.6,293.5,297.8
XS GIS Cut Line= 2
2265534.38875575415495.801078248 2265273.0272892415992.891661971
#Sta/Elev= 30
       0 2432.89    46.7 2427.07     101 2422.07   150.8  2414.9   173.3  2410.7
   186.8 2410.69   236.6 2406.67   245.6 2403.91   263.3 2394.45281.68882390.455
     290 2388.54   298.8 2388.25   308.9 2388.51314.68752390.206   326.9 2395.99
     361 2398.35   367.6 2397.47   382.9 2390.92   385.7 2391.04   393.6 2394.53
   396.6 2394.89   417.3 2394.84   426.4 2393.47   453.5 2394.46   476.6 2391.47
   488.4 2393.07   498.7 2393.11   515.1 2403.42   526.9 2413.49   561.6  2437.6
#Mann= 4 ,-1,0
       0     .12       0281.6888    .045       0314.6875     .07       0
     420      .1       0
#XS Ineff= 1 ,-1
  353.58   521.9 2402.79
Permanent Ineff=
       F
Bank Sta=281.6888,314.6875
XS Rating Curve= 0 ,0
Exp/Cntr(USF)=0,0
Exp/Cntr=0.3,0.1

Type RM Length L Ch R = 1 ,8146    ,324.3,332.5,339.9
XS GIS Cut Line= 2
2265346.02813774415362.8525080742265005.94990065415773.851254988
#Sta/Elev= 30
       0 2466.91      29 2460.89   102.4 2440.73   159.2 2423.49   178.6 2419.75
   218.9 2409.39   235.1 2403.83   252.2 2393.58   258.7 2392.72   266.4 2390.45
     270 2390.39281.8097 2389.84   288.6 2387.93   309.8 2387.81   314.5 2388.25
 318.1772389.895   324.9  2393.1   360.6 2395.74   372.3 2393.02   397.6 2392.15
     408    2389   417.8 2387.51   428.7 2388.04   439.1 2391.04   459.9 2391.17
   466.1 2393.31   475.5 2399.29   494.5 2400.37   511.5 2411.28   533.5 2420.55
#Mann= 6 ,-1,0
       0     .12       0     220     .07       0     270     .08       0
281.8097    .045       0 318.177     .08       0     380      .1       0
#XS Ineff= 2 , 0
                          359.32         2399.76
Permanent Ineff=
       F       F
Bank Sta=281.8097,318.177
XS Rating Curve= 0 ,0
Exp/Cntr(USF)=0,0
Exp/Cntr=0.3,0.1

Type RM Length L Ch R = 1 ,7814    ,277.9,271.9,264.7
XS GIS Cut Line= 3
 2265187.2809569415100.1736454382265037.22309364 415282.67301742
 2264768.9056079415443.782120191
#Sta/Elev= 30
       0 2570.14    42.7 2547.21    63.4 2534.89    84.2 2524.15    94.5 2517.73
   122.3 2503.21   162.1 2480.53   184.8  2466.2   204.7 2454.93   256.2 2421.44
   270.2 2411.19   279.7 2401.13   288.8 2389.88 293.4762386.088   297.2 2384.75
   302.8 2384.62   321.5 2384.99   326.1 2386.21   330.8 2388.24   340.9 2388.87
   393.4 2386.73   407.9 2391.61   425.4 2392.85   450.9 2391.75   466.1 2387.04
   475.4 2388.25   489.6  2388.7   494.1 2389.99   515.8 2399.64   549.2 2410.01
#Mann= 5 ,-1,0
       0      .1       0 293.476    .045       0   326.1      .1       0
  386.27     .06       0  506.27      .1       0
#XS Ineff= 1 ,-1
  426.76   497.5 2429.15
Permanent Ineff=
       F
Bank Sta=293.476,326.1
XS Rating Curve= 0 ,0
Exp/Cntr(USF)=0,0
Exp/Cntr=0.3,0.1

Type RM Length L Ch R = 1 ,7542    ,293.5,287.5,280.9
XS GIS Cut Line= 2
2264997.26101894414877.3093673662264672.08888275415272.027984354
#Sta/Elev= 30
       0 2565.37    20.6 2554.78    56.8 2534.83    67.2 2529.94   131.4 2496.37
   170.9 2473.61   196.8 2458.02   212.3 2443.85   236.5 2424.35   253.8 2411.57
   274.5 2391.17 284.4992383.697   291.1 2382.02   300.4 2381.81   305.6 2382.13
310.69892383.635   316.1 2384.35   347.4 2383.79     353 2384.12   361.6 2385.66
     390 2385.52   398.9 2385.77   424.8 2384.23   435.8 2384.62     444  2386.1
   455.9 2391.21   461.1 2392.16   497.4 2389.75   500.8 2391.22   511.4 2397.86
#Mann= 8 ,-1,0
       0     .12       0     130      .1       0     140     .12       0
     260      .1       0 284.499    .045       0310.6989      .1       0
     390     .06       0     510      .1       0
#XS Ineff= 2 , 0
                          470.54         2412.23
Permanent Ineff=
       F       F
Bank Sta=284.499,310.6989
XS Rating Curve= 0 ,0
Exp/Cntr(USF)=0,0
Exp/Cntr=0.3,0.1

Type RM Length L Ch R = 1 ,7254    ,350,330.8,308.4
XS GIS Cut Line= 3
2264745.35964485 414630.862117442264498.21066479415113.038225875
2264479.42387929415262.540868732
#Sta/Elev= 30
       0  2609.6    11.6 2601.39    47.6 2580.03      70 2565.44   133.4 2519.34
   154.2 2501.02   186.8 2465.72   249.8 2416.91   267.8  2401.4   284.9 2384.26
289.69972382.073   299.8 2380.64   326.2 2380.78332.29972381.871   366.7 2386.97
   411.6 2384.69   461.1 2384.19     487 2388.22   507.8 2394.88   537.5 2396.16
   568.8 2394.93   578.3 2393.26   586.3 2390.28   626.6  2387.4   638.7 2399.96
   654.8 2414.82     671 2427.22     679 2430.84   682.6 2434.12   692.5 2448.09
#Mann= 8 ,-1,0
       0      .1       0     280     .12       0289.6997    .045       0
332.2997     .12       0     390      .1       0     500     .06       0
     510     .07       0  601.83      .1       0
Bank Sta=289.6997,332.2997
XS Rating Curve= 0 ,0
Exp/Cntr(USF)=0,0
Exp/Cntr=0.3,0.1

Type RM Length L Ch R = 1 ,6924    ,388.7,374.7,361.3
XS GIS Cut Line= 3
2264243.57132979414723.6339617212264328.56305052415020.265696862
2264345.18448613415161.291008121
#Sta/Elev= 30
       0 2447.54    14.7 2441.86    22.4 2438.01    53.5 2421.48    68.2 2412.69
    80.7 2406.86    97.3 2395.82   109.8 2390.78   118.1 2386.43   126.4 2383.73
   134.8 2382.39   151.4 2383.92     157 2383.82   159.7  2383.3   170.5 2378.39
   180.5 2377.32   201.3 2377.09   213.8 2377.17   221.7 2378.28   237.8 2381.26
   259.6 2382.37   276.2 2382.39     297 2385.83   333.7 2385.95   369.9 2384.76
     390 2386.05   406.2 2390.35   422.3 2389.84   438.4 2388.53   450.6 2388.53
#Mann= 6 ,-1,0
       0      .1       0     160     .12       0   170.5    .045       0
   221.7     .12       0     280      .1       0  368.57     .06       0
Bank Sta=170.5,221.7
XS Rating Curve= 0 ,0
Exp/Cntr(USF)=0,0
Exp/Cntr=0.3,0.1

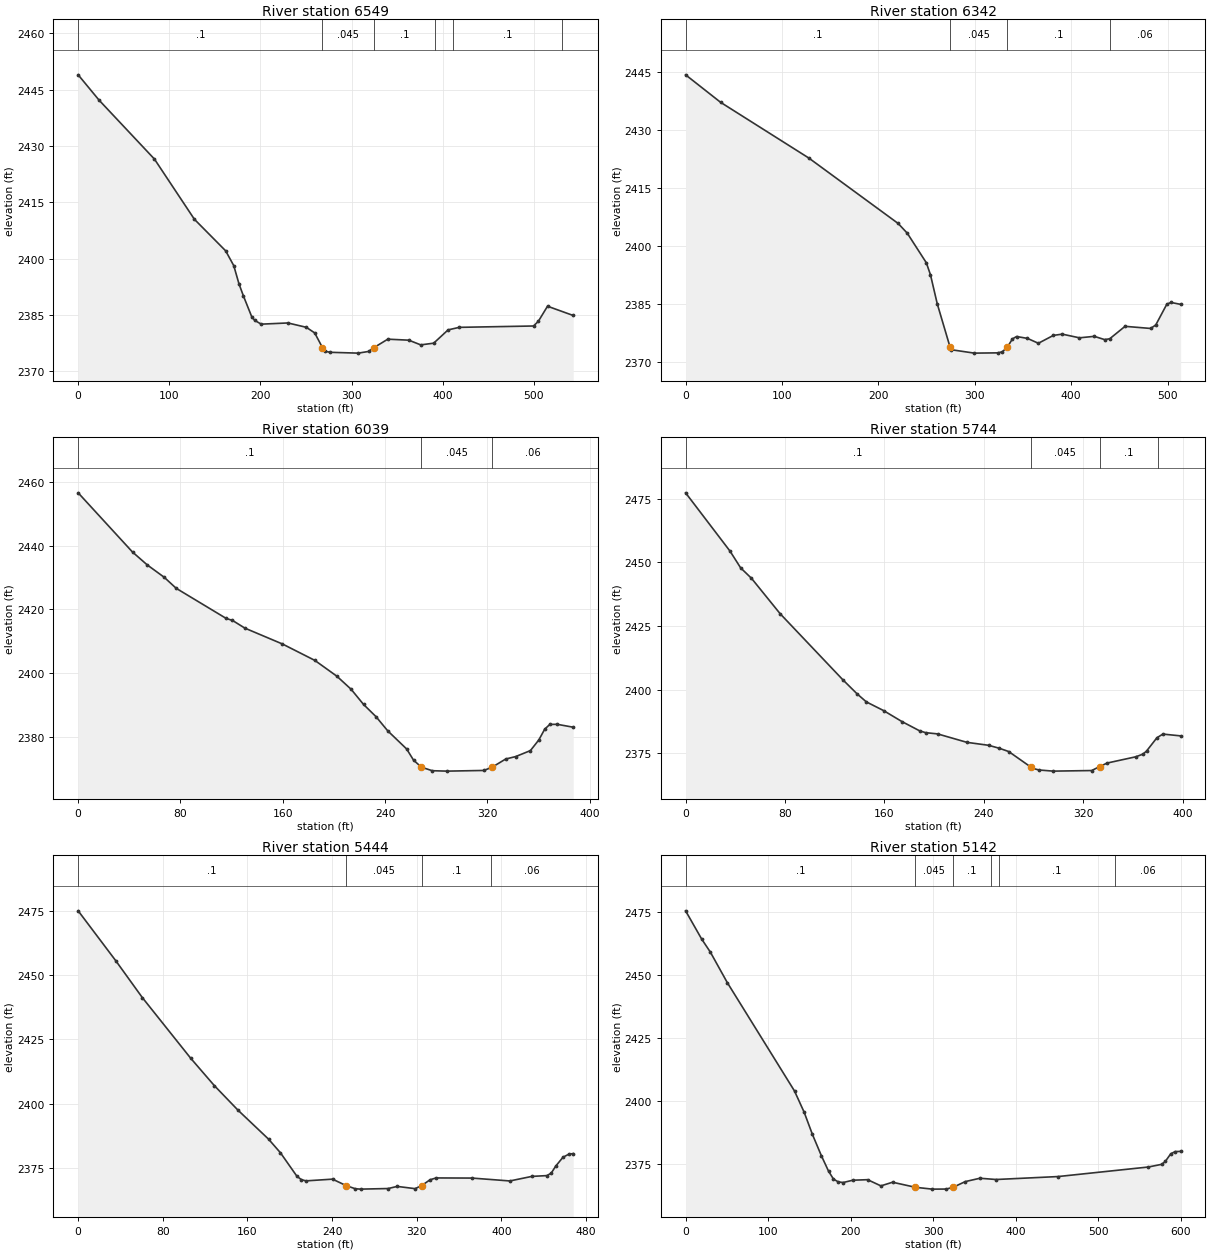
Type RM Length L Ch R = 1 ,6549    ,212,207.1,202.4
XS GIS Cut Line= 4
2263791.05614033414844.615678679 2263929.3589864415042.296553206
2264065.05537749415201.2551827672264109.75606184 415282.57848368
#Sta/Elev= 30
       0 2448.97    22.9 2442.23    83.7 2426.51   127.5 2410.48   161.8 2402.07
   170.7 2398.12   176.4 2393.28   181.3 2390.04   190.3 2384.57   193.6 2383.55
   200.8 2382.53   230.1 2382.85   250.3 2381.69   259.5 2380.19     268 2376.28
   271.3 2375.29   276.4 2375.03   307.2 2374.81   318.7 2375.26324.53722376.292
   339.7 2378.53   362.7 2378.26   375.8 2377.01     390 2377.46   405.8    2381
   418.1 2381.68   499.6 2382.04   504.9 2383.32   514.9 2387.31   543.1 2384.84
#Mann= 6 ,-1,0
       0      .1       0     268    .045       0324.5372      .1       0
  391.26     .12       0  411.26      .1       0  530.26     .06       0
Bank Sta=268,324.5372
XS Rating Curve= 0 ,0
Exp/Cntr(USF)=0,0
Exp/Cntr=0.3,0.1

Type RM Length L Ch R = 1 ,6342    ,304,303.3,295.8
XS GIS Cut Line= 2
2263596.81839275415036.204561912 2263983.6660959415373.948884729
#Sta/Elev= 30
       0 2444.31    36.3  2437.2   127.8 2422.79   220.4 2405.88   229.9 2403.36
   249.7  2395.7     254 2392.58     261 2385.11   274.22373.974   275.3 2373.22
   299.5 2372.33   323.8  2372.4   328.4 2372.67   333.62373.814     339 2376.01
   343.3 2376.63   354.6 2376.14   365.9 2374.88   381.5 2376.92   390.7 2377.24
   408.5 2376.29   423.9 2376.67   434.6 2375.83   439.9 2376.04   455.8 2379.26
   482.4 2378.71   487.7 2379.63   499.2 2385.01   503.6 2385.43   513.5 2384.94
#Mann= 4 ,-1,0
       0      .1       0   274.2    .045       0   333.6      .1       0
     440     .06       0
Bank Sta=274.2,333.6
XS Rating Curve= 0 ,0
Exp/Cntr(USF)=0,0
Exp/Cntr=0.3,0.1

Type RM Length L Ch R = 1 ,6039    ,293,294.4,290.7
XS GIS Cut Line= 2
2263489.34745965  415350.21568082263806.45119872415572.429569562
#Sta/Elev= 30
       0 2456.58    42.5    2438      54 2433.97    67.3 2430.08    76.7 2426.61
   115.8 2417.16   120.7 2416.54   130.4 2414.12   159.8 2409.14   185.1    2404
   202.3 2399.05   213.5 2394.93   223.2 2390.18     233 2386.32   242.1  2381.9
   256.9 2376.21   262.3  2372.7   268.4 2370.51   276.9 2369.38   288.5 2369.25
   317.2 2369.46323.5789 2370.44   334.4 2373.05   342.2 2373.82   353.7 2375.69
   360.3 2379.04   364.9 2382.42   368.9 2383.91   374.7 2383.94   387.2 2383.03
#Mann= 3 ,-1,0
       0      .1       0   268.4    .045       0323.5789     .06       0
Bank Sta=268.4,323.5789
XS Rating Curve= 0 ,0
Exp/Cntr(USF)=0,0
Exp/Cntr=0.3,0.1

Type RM Length L Ch R = 1 ,5744    ,290.3,299.9,305
XS GIS Cut Line= 2
2263314.19670001415593.8669520222263648.13922392415811.078964422
#Sta/Elev= 30
       0 2477.36    35.8 2454.39    44.3 2447.84      53 2443.75    76.1  2429.8
   126.4  2403.9   138.1 2398.25   145.5 2395.12   159.3 2391.72   174.1 2387.39
   188.5 2383.71   193.2 2383.03   202.8 2382.54   226.4 2379.22   243.8 2378.06
   252.5 2376.89     260 2375.61277.59322369.577   279.1 2369.04   284.3 2368.35
   295.8  2367.9   326.8 2368.13333.09192369.666   339.2 2371.07   362.3 2373.54
   368.1  2374.6     371 2375.83   379.3 2381.03   384.1 2382.47   398.4 2381.76
#Mann= 4 ,-1,0
       0      .1       0277.5932    .045       0333.0919      .1       0
     380     .06       0
Bank Sta=277.5932,333.0919
XS Rating Curve= 0 ,0
Exp/Cntr(USF)=0,0
Exp/Cntr=0.3,0.1

Type RM Length L Ch R = 1 ,5444    ,303.9,302.2,300.7
XS GIS Cut Line= 2
2263176.09015299415786.8701567772263511.09303677416113.525722264
#Sta/Elev= 30
       0 2474.96    35.6 2455.52    60.6 2441.24   106.3 2417.66   128.6 2407.03
     151 2397.46   179.9 2386.19   191.2 2380.86   206.8 2371.71     211 2370.42
   215.3 2369.94   240.4 2370.61253.29362368.099   261.9 2366.88   266.9 2366.73
     293 2366.96   301.5 2367.79   318.5 2366.91  324.722368.137   332.6 2370.37
   338.3 2371.08   372.2 2371.03     408 2369.91   428.8 2371.68     443 2371.99
   447.1 2372.95   451.4  2375.7   458.2 2379.12   463.8 2380.33   467.9 2380.55
#Mann= 4 ,-1,0
       0      .1       0253.2936    .045       0  324.72      .1       0
     390     .06       0
Bank Sta=253.2936,324.72
XS Rating Curve= 0 ,0
Exp/Cntr(USF)=0,0
Exp/Cntr=0.3,0.1

Type RM Length L Ch R = 1 ,5142    ,298.9,298,298
XS GIS Cut Line= 2
2262958.93374791416004.0525580262263401.03865435416409.691870344
#Sta/Elev= 30
       0 2475.52    19.4 2464.35      30 2459.13    50.5 2447.04     132 2403.98
   143.7 2395.55   153.7 2386.75   164.5 2378.34   173.2 2372.19   179.2 2369.02
   185.1 2367.89     191 2367.66   202.7 2368.57   220.6 2368.78   236.7 2366.32
   250.8 2367.77   278.5 2365.76   298.9 2365.03   315.9 2365.06   324.4 2365.78
   338.9 2368.02   356.7 2369.35   376.3 2368.85   451.3 2370.02   560.8 2373.81
   577.1 2374.88   581.5 2376.08     588 2379.06   593.4 2379.94     600 2380.01
#Mann= 6 ,-1,0
       0      .1       0   278.5    .045       0   324.4      .1       0
     370     .12       0     380      .1       0     520     .06       0
Bank Sta=278.5,324.4
XS Rating Curve= 0 ,0
Exp/Cntr(USF)=0,0
Exp/Cntr=0.3,0.1

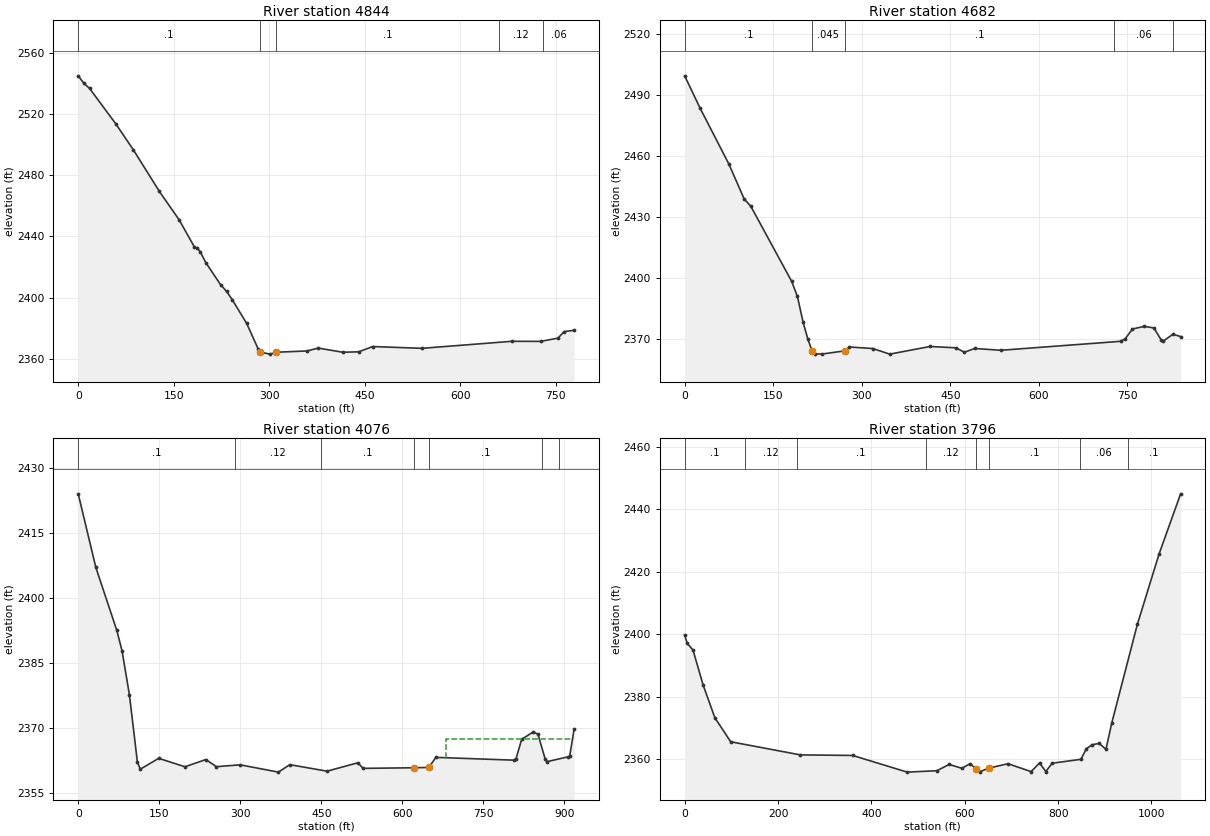
Type RM Length L Ch R = 1 ,4844    ,160.1,161.9,165
XS GIS Cut Line= 2
 2262660.5087943 416196.741996822263342.40319526416572.463515217
#Sta/Elev= 30
       0 2545.24     8.8  2540.4    17.9 2536.96    59.1 2513.75    86.4 2496.87
   127.5 2469.47   158.4 2450.93   182.3 2433.23   186.9 2432.34   191.5 2430.01
   200.6 2422.69   223.4  2408.5     233 2403.99   242.2 2398.31   264.5 2383.03
   282.8 2366.08   285.7 2364.27     301 2362.92311.2932 2364.17   359.3    2365
     377 2366.88   415.2 2364.16   440.2 2364.42   462.4 2367.89   539.7 2366.72
   680.6 2371.32   725.8 2371.27   753.2 2373.38   762.7 2377.66   778.6 2378.56
#Mann= 5 ,-1,0
       0      .1       0   285.7    .045       0311.2932      .1       0
     660     .12       0     730     .06       0
Bank Sta=285.7,311.2932
XS Rating Curve= 0 ,0
Exp/Cntr(USF)=0,0
Exp/Cntr=0.3,0.1

Type RM Length L Ch R = 1 ,4682    ,627.6,605.8,581.6
XS GIS Cut Line= 3
2262635.91891864416337.2077734392263165.51291385416709.221584737
2263357.18187593 416685.55153193
#Sta/Elev= 30
       0 2499.58      26 2483.73    74.8  2456.2   100.7 2439.01   112.1 2435.33
   181.1 2398.49     191 2390.97   200.7 2378.18   208.7 2369.96   215.7 2364.25
   220.3 2362.66   232.7 2362.61   271.3 2364.17   278.9 2366.08   318.9 2365.31
   347.4 2362.56   415.8 2366.33   459.6 2365.66   473.9 2363.48   491.2 2365.34
   535.8 2364.46   738.5 2368.87   746.5 2370.15   758.7 2374.93   778.8 2376.22
     795 2375.46   807.1  2369.7   811.1    2369   827.2 2372.34   840.3 2371.22
#Mann= 5 ,-1,0
       0      .1       0   215.7    .045       0   271.3      .1       0
   727.2     .06       0   827.2      .1       0
Bank Sta=215.7,271.3
XS Rating Curve= 0 ,0
Exp/Cntr(USF)=0,0
Exp/Cntr=0.3,0.1

Type RM Length L Ch R = 1 ,4076    ,274.7,280.1,289
XS GIS Cut Line= 4
2262409.30619279416691.6361551162262913.07639269417037.173304536
2262971.33097449417041.4884587442263191.54694246417156.817678169
#Sta/Elev= 30
       0 2424.14    32.6 2407.12    71.4 2392.56    81.1 2387.84    94.7 2377.71
   109.6 2362.04     115 2360.46     149 2362.96   197.5 2361.01   236.2 2362.68
   255.7 2361.03   299.7 2361.46   370.5 2359.77   391.6  2361.5   460.6 2359.99
   517.6 2361.93   527.3 2360.64   621.3 2360.78   648.9 2360.85   661.9 2363.18
     806 2362.54   810.2 2362.81   820.8 2367.37   841.8 2369.03   850.9 2368.57
   864.4 2362.73   868.2 2362.21   906.8 2363.31   909.6 2363.45   917.9 2369.75
#Mann= 7 ,-1,0
       0      .1       0     290     .12       0     450      .1       0
   621.3    .045       0   648.9      .1       0   859.3     .06       0
   889.3      .1       0
#XS Ineff= 2 , 0
                             680          2367.5
Permanent Ineff=
       F       F
Bank Sta=621.3,648.9
XS Rating Curve= 0 ,0
Exp/Cntr(USF)=0,0
Exp/Cntr=0.3,0.1

Type RM Length L Ch R = 1 ,3796    ,377.9,382.8,387.1
XS GIS Cut Line= 4
2262346.56258599  416819.9621671 2262433.1647618417071.968230807
2262977.80370581417352.1795617112263152.41133452417408.803339777
#Sta/Elev= 30
       0 2399.66     5.4 2397.14      18 2394.89    39.4 2383.81    64.7 2373.28
    98.6  2365.6   247.8  2361.4   359.8 2361.22   476.8 2355.88   540.2 2356.33
   566.7 2358.35   593.7  2357.1   611.7 2358.59   623.1 2357.02     632 2355.98
651.58792357.162   692.7 2358.57   742.2 2356.05   760.2 2358.79   773.7 2356.08
   787.2 2358.73   848.8 2359.98   860.7 2363.38   872.6 2364.63     888 2365.09
   902.5 2363.17   915.1 2371.68   969.8 2403.15    1016 2425.56  1062.5 2444.96
#Mann= 8 ,-1,0
       0      .1       0     130     .12       0     240      .1       0
  516.47     .12       0   623.1    .045       0651.5879      .1       0
  846.47     .06       0  948.97      .1       0
Bank Sta=623.1,651.5879
XS Rating Curve= 0 ,0
Exp/Cntr(USF)=0,0
Exp/Cntr=0.3,0.1