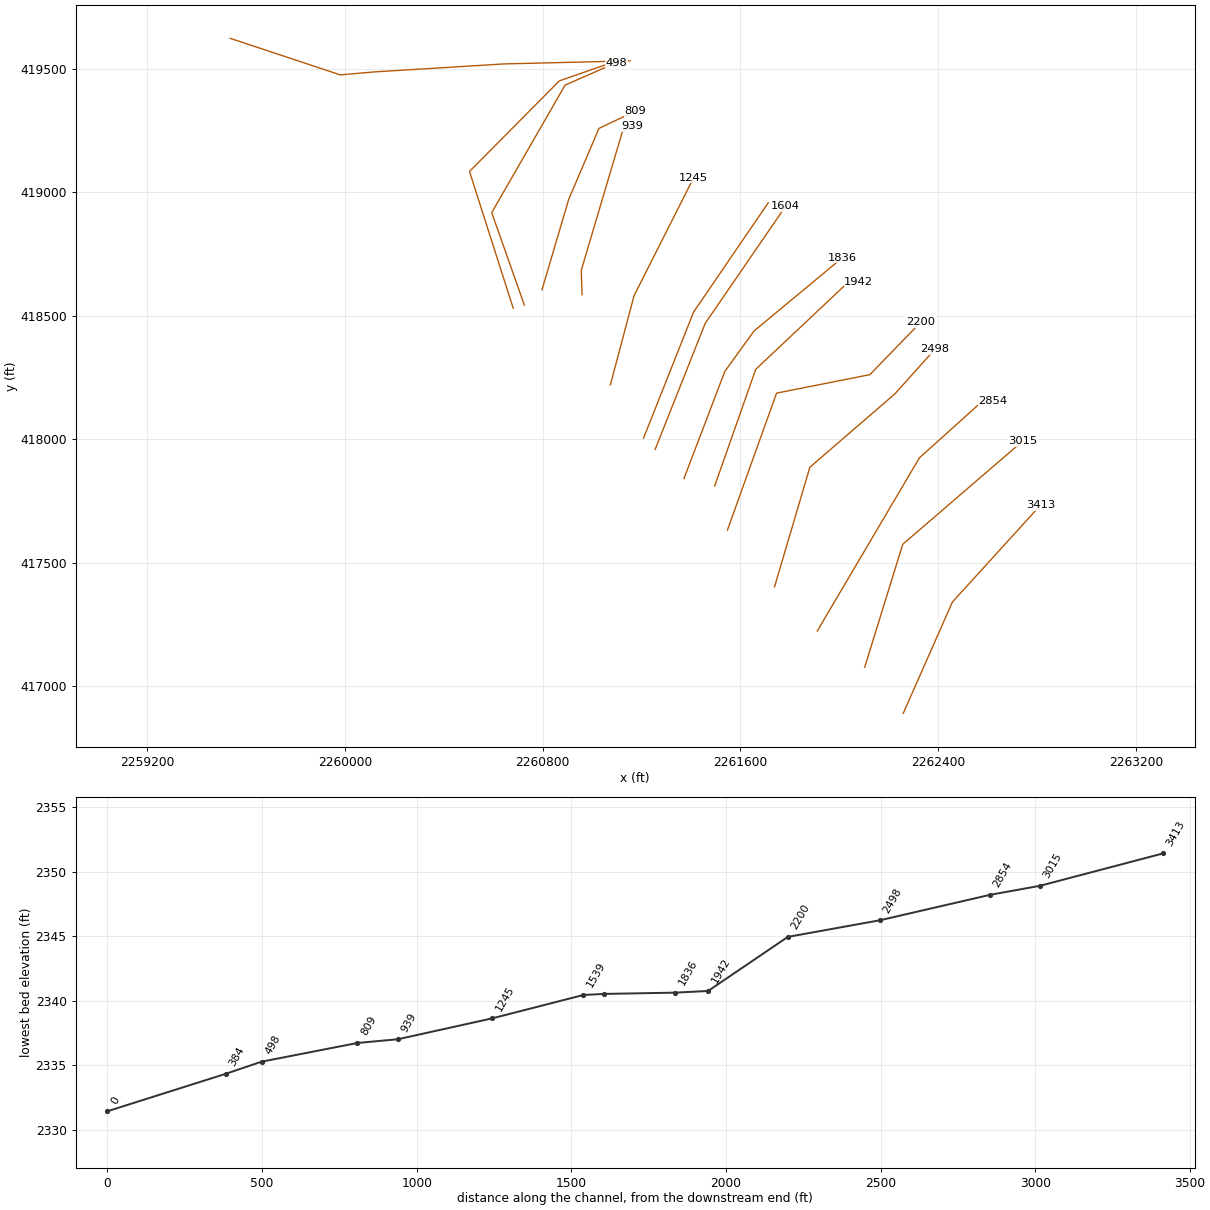
HEC-RAS study LAURELCK.prj: LAURELCK

--- LAURELCK.g01 (geometry) --- (continued)

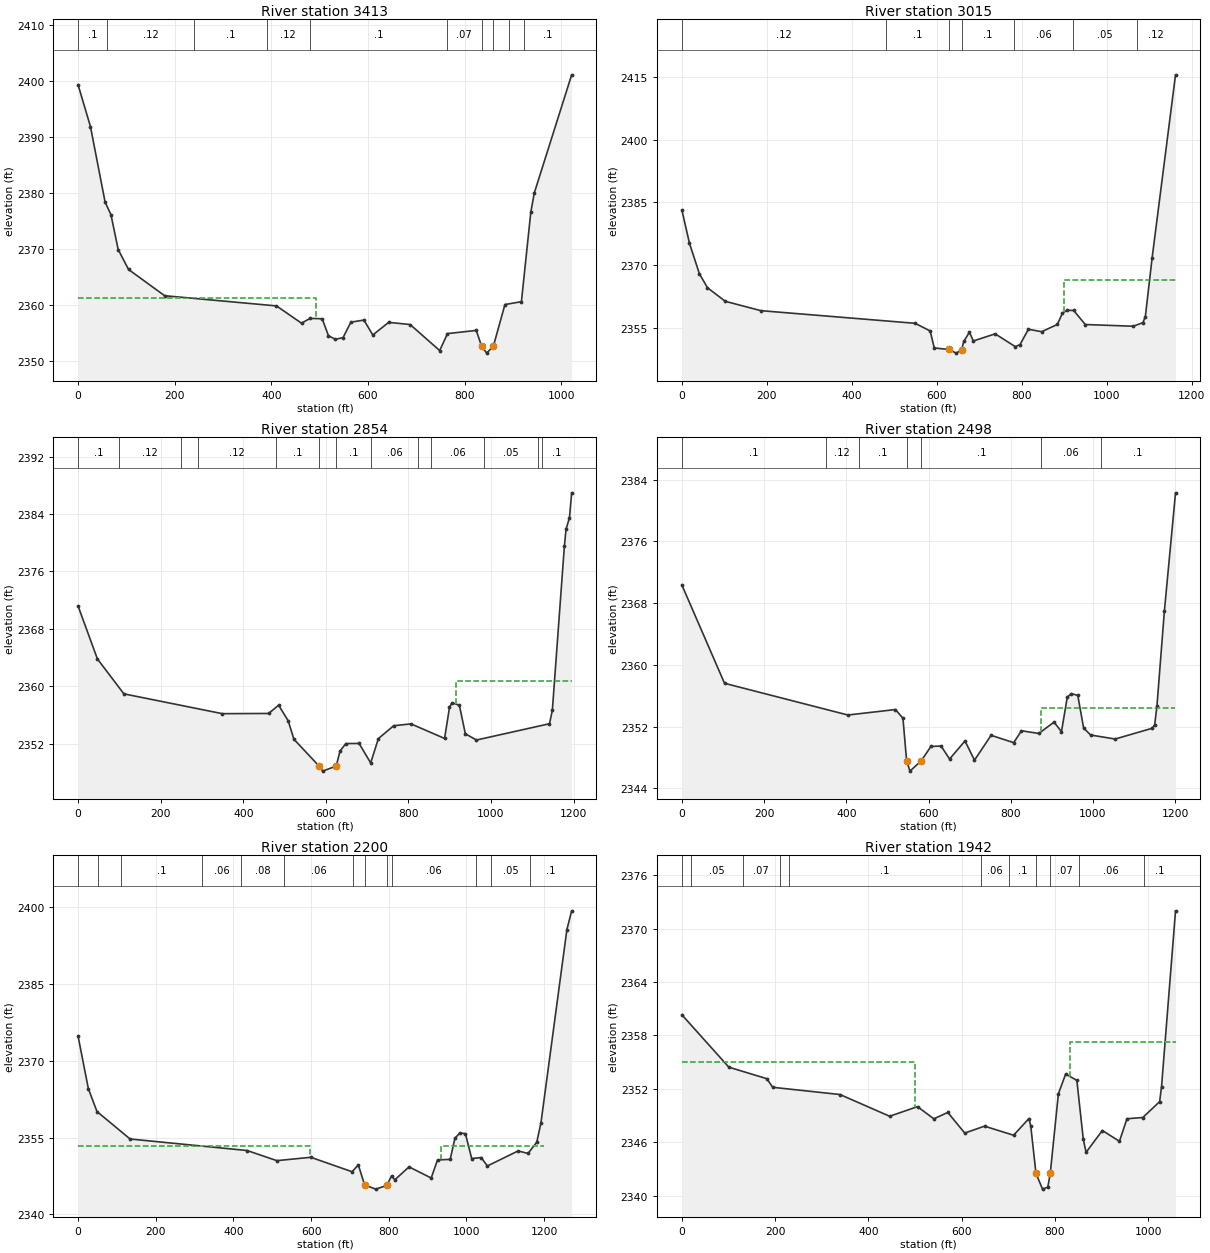
Type RM Length L Ch R = 1 ,3413    ,404.4,398,396.8
XS GIS Cut Line= 3
2262258.39861426416889.2318576822262457.25511491417339.852810701
2262813.04044284417731.252962216
#Sta/Elev= 30
       0 2399.36    25.6  2391.9    55.9  2378.4      68 2376.16      83 2369.92
   104.4 2366.36   179.2 2361.67   410.6 2359.85   462.4 2356.76     480 2357.62
   505.2 2357.55   518.2 2354.51   532.6 2353.88   548.4 2354.19   564.6 2356.95
   591.6 2357.32   609.9 2354.65   642.8 2356.91   687.2 2356.52   748.4 2351.87
   764.5  2354.9   824.1 2355.47   834.9 2352.68   845.7 2351.41   859.6  2352.7
   883.4 2360.09   917.5 2360.61   936.9 2376.57   944.1 2380.02  1021.5 2401.15
#Mann= 10 ,-1,0
       0      .1       0      60     .12       0     240      .1       0
     390     .12       0     480      .1       0  762.55     .07       0
   834.9    .045       0   859.6     .07       0  892.55     .06       0
  922.55      .1       0
#XS Ineff= 2 , 0
          492.17 2361.27
Permanent Ineff=
       F       F
Bank Sta=834.9,859.6
XS Rating Curve= 0 ,0
Exp/Cntr(USF)=0,0
Exp/Cntr=0.3,0.1

Type RM Length L Ch R = 1 ,3015    ,153.2,161.4,167.1
XS GIS Cut Line= 3
2262102.46954485417075.7660072812262256.41156478 417573.77647497
2262741.92880246417991.692348827
#Sta/Elev= 30
       0 2383.08    17.7 2375.21    40.9 2367.94    60.1 2364.56     102 2361.31
   185.7 2359.07     549 2356.04   584.3 2354.21   593.9 2350.14   628.4 2349.77
   645.5  2348.9   658.2 2349.68   663.4  2351.7   676.7 2353.91   685.9 2351.81
   737.3 2353.52   784.8 2350.45   795.8 2350.94   815.6 2354.62   846.8 2354.03
   883.7 2355.77   895.7 2358.49   906.4 2359.16   922.1 2359.12   949.5 2355.75
  1062.4 2355.34  1085.1  2356.2  1090.8  2357.6  1106.8 2371.72  1161.9 2415.55
#Mann= 7 ,-1,0
       0     .12       0     480      .1       0   628.4    .045       0
   658.2      .1       0  781.26     .06       0  921.26     .05       0
 1071.26     .12       0
#XS Ineff= 2 , 0
                          899.83         2366.46
Permanent Ineff=
       F       F
Bank Sta=628.4,658.2
XS Rating Curve= 0 ,0
Exp/Cntr(USF)=0,0
Exp/Cntr=0.3,0.1

Type RM Length L Ch R = 1 ,2854    ,362.4,356,351.3
XS GIS Cut Line= 4
2261910.73753381417222.7290950682262324.05784331417923.937494255
2262561.39132475418137.5376275442262621.21874191418154.166123675
#Sta/Elev= 30
       0 2371.18    46.7 2363.83   110.9 2358.96   349.4  2356.2   461.5 2356.23
   485.7 2357.38   508.9  2355.2   522.7 2352.64   584.12348.876   592.5  2348.2
   625.22348.911   634.3 2350.98   648.4 2352.04   680.6 2352.05   708.6 2349.34
   727.3 2352.73   764.3 2354.52   806.2 2354.78   887.6 2352.75   899.5 2357.06
   905.5 2357.72   923.4 2357.38   937.9  2353.4   964.8 2352.53  1141.7  2354.8
  1148.6 2356.66  1177.7 2379.49  1181.8 2381.89  1190.1 2383.49  1195.4 2386.95
#Mann= 13 ,-1,0
       0      .1       0     100     .12       0     250      .1       0
     290     .12       0     480      .1       0   584.1    .045       0
   625.2      .1       0     710     .06       0  823.96      .1       0
  853.96     .06       0  983.96     .05       0 1113.96     .12       0
 1123.96      .1       0
#XS Ineff= 2 , 0
                          914.14         2360.74
Permanent Ineff=
       F       F
Bank Sta=584.1,625.2
XS Rating Curve= 0 ,0
Exp/Cntr(USF)=0,0
Exp/Cntr=0.3,0.1

Type RM Length L Ch R = 1 ,2498    ,309.4,298,289.5
XS GIS Cut Line= 4
2261737.89287303417401.8371293432261880.71598278417885.674693994
2262224.80929653418182.8467467272262386.28150728418362.977372918
#Sta/Elev= 30
       0 2370.32   103.6 2357.61   403.7  2353.5   519.6 2354.21   537.8 2353.07
   546.6 2347.58   554.8 2346.23  582.58 2347.59   605.8 2349.43   630.6 2349.48
   651.2  2347.8   688.7 2350.14   711.8 2347.65   752.2 2350.87   807.2 2349.92
   826.2 2351.46   868.4 2351.11   905.4 2352.58   923.5 2351.34   937.6 2355.82
   947.7 2356.28   963.2 2356.03   977.3 2351.83   994.3 2350.91  1054.1 2350.39
  1144.5 2351.79  1150.3 2352.25  1155.8 2354.67  1173.9 2366.99    1201 2382.29
#Mann= 7 ,-1,0
       0      .1       0     350     .12       0     430      .1       0
   546.6    .045       0  582.58      .1       0  874.48     .06       0
 1019.13      .1       0
#XS Ineff= 1 ,-1
  873.24    1200  2354.4
Permanent Ineff=
       F
Bank Sta=546.6,582.58
XS Rating Curve= 0 ,0
Exp/Cntr(USF)=0,0
Exp/Cntr=0.3,0.1

Type RM Length L Ch R = 1 ,2200    ,246.8,257.8,269.9
XS GIS Cut Line= 4
2261547.24991265 417631.417930622261746.03266093418185.758586541
2262123.40317265418260.5195224692262330.28653273 418473.99163213
#Sta/Elev= 30
       0  2374.8    26.4 2364.57    48.6  2360.1   133.9 2354.73   435.3 2352.48
   511.8  2350.5   599.2 2351.16   705.3 2348.34   721.6 2349.66737.69652345.767
   766.4 2344.94794.69512345.651   807.2 2347.52   815.4 2346.75   852.1 2349.29
   909.2 2347.11   925.5 2350.64   958.1 2350.75   970.3 2354.87   983.1 2355.91
   997.3 2355.77  1013.5 2350.91  1037.9 2351.11  1053.8 2349.46    1133  2352.4
  1158.5 2351.91  1181.1 2354.12  1191.8 2357.88  1258.6 2395.63  1270.9  2399.3
#Mann= 13 ,-1,0
       0      .1       0      50     .12       0     110      .1       0
     320     .06       0     420     .08       0     530     .06       0
   708.9      .1       0737.6965    .045       0794.6951      .1       0
   808.9     .06       0 1023.61      .1       0 1063.61     .05       0
 1163.61      .1       0
#XS Ineff= 2 ,-1
       0  596.06 2353.42  934.31    1200 2353.35
Permanent Ineff=
       F       F
Bank Sta=737.6965,794.6951
XS Rating Curve= 0 ,0
Exp/Cntr(USF)=0,0
Exp/Cntr=0.3,0.1

Type RM Length L Ch R = 1 ,1942    ,108.1,106.7,105.6
XS GIS Cut Line= 4
 2261495.5482354417809.585907746 2261661.6816724418282.095293508
2262039.25766559418638.0955156582262078.09405346 418633.78036145
#Sta/Elev= 30
       0 2360.31   100.6 2354.44   181.9 2353.15   194.8 2352.18     339 2351.37
   445.6 2348.93   505.4 2350.01   540.3 2348.64   570.3 2349.36   606.7 2347.04
   649.1 2347.82   711.4  2346.8   744.4 2348.67   748.2 2347.88   759.5 2342.51
   773.6 2340.75   784.9 2340.98   790.2 2342.54   807.6 2351.46   823.2 2353.67
   847.2 2352.96     861 2346.35     867 2344.88   901.9 2347.33   938.6 2346.12
   954.7 2348.65   988.7 2348.79  1024.8 2350.57  1028.9 2352.26  1058.9 2371.99
#Mann= 11 ,-1,0
       0      .1       0      20     .05       0     130     .07       0
     210     .06       0     230      .1       0  640.86     .06       0
  700.86      .1       0   759.5    .045       0   790.2     .07       0
  850.86     .06       0  990.86      .1       0
#XS Ineff= 2 , 0
             500    2355   832.9         2357.31
Permanent Ineff=
       F       F
Bank Sta=759.5,790.2
XS Rating Curve= 0 ,0
Exp/Cntr(USF)=0,0
Exp/Cntr=0.3,0.1

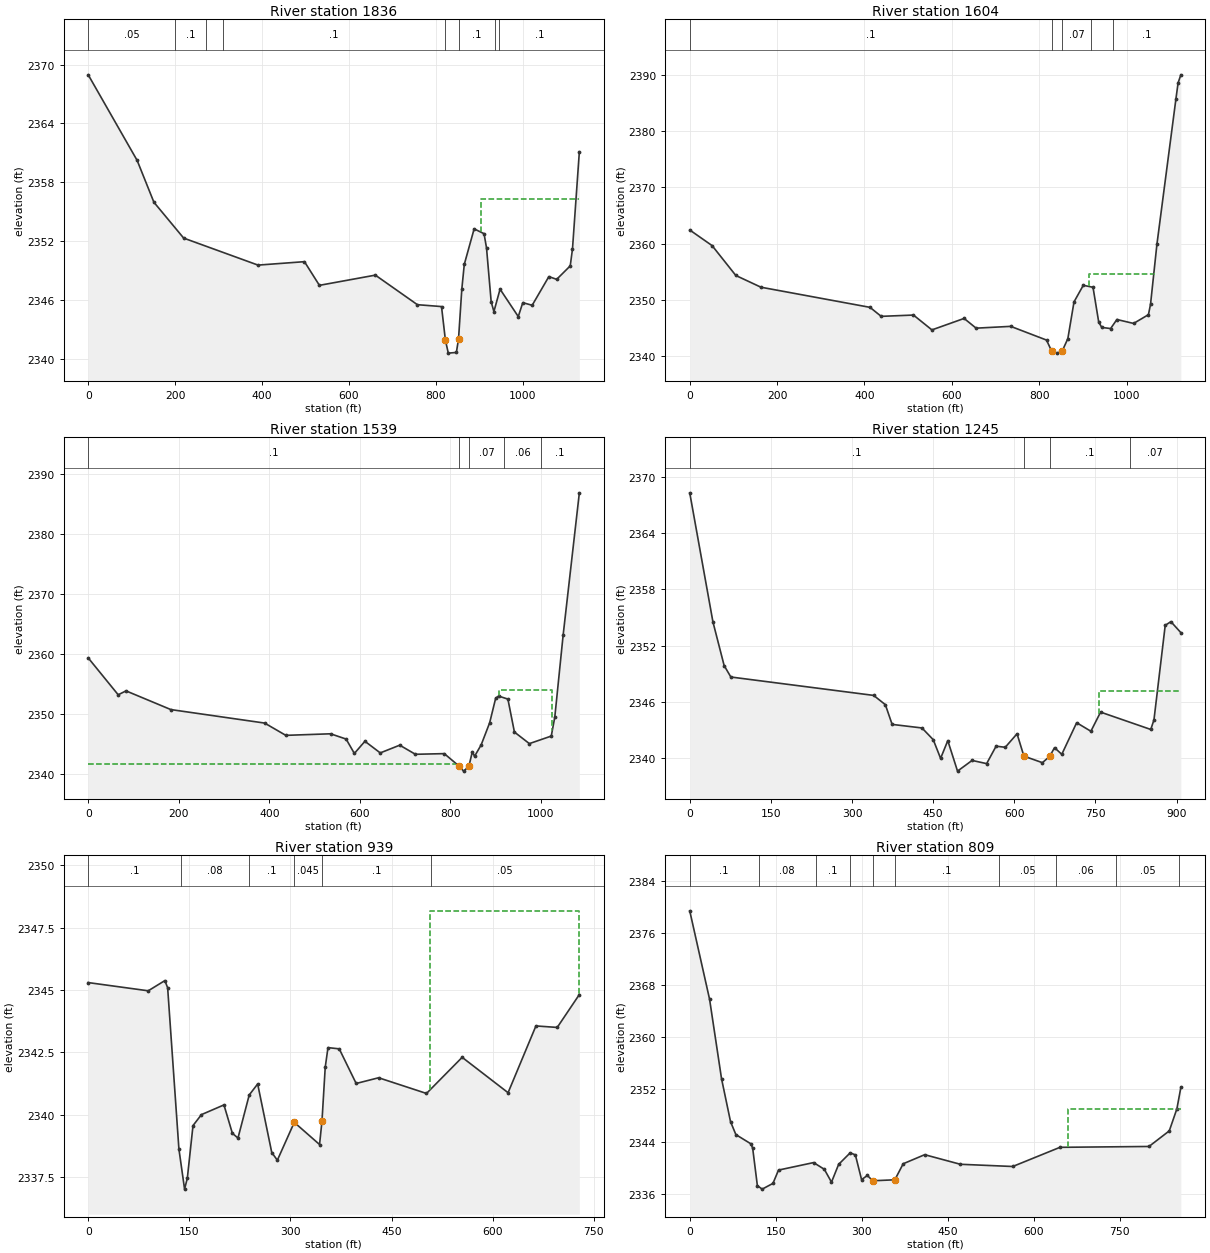
Type RM Length L Ch R = 1 ,1836    ,225.9,231.1,235.9
BEGIN DESCRIPTION:
structure xs 4
END DESCRIPTION:
XS GIS Cut Line= 4
2261371.43157529417839.9035366782261536.54220037418273.464985093
2261654.91555972418437.3575462062262012.38241467418733.995948266
#Sta/Elev= 30
       0 2368.95   112.7 2360.23   151.2 2355.98   219.7 2352.33   390.9 2349.58
   497.8 2349.93   532.2 2347.52     661 2348.56   757.8 2345.55   813.3 2345.36
822.21942341.952   828.9 2340.62   847.5 2340.69852.43622342.043     860 2347.12
   865.7 2349.65   888.4 2353.27   911.2 2352.78   916.9 2351.33   927.6 2345.86
   933.9 2344.85   948.1 2347.13     990 2344.34  1000.4 2345.76    1022 2345.49
  1060.4 2348.41  1078.4 2348.13  1109.6  2349.5  1114.8 2351.22  1130.6 2361.12
#Mann= 8 ,-1,0
       0     .05       0     200      .1       0     270     .05       0
     310      .1       0822.2194    .045       0852.4362      .1       0
  936.11     .06       0  946.11      .1       0
#XS Ineff= 2 , 0
                          903.21         2356.34
Permanent Ineff=
       F       F
Bank Sta=822.2194,852.4362
XS Rating Curve= 0 ,0
Exp/Cntr(USF)=0,0
Exp/Cntr=0.5,0.3

Type RM Length L Ch R = 1 ,1604    ,65.2,65.2,65.3
BEGIN DESCRIPTION:
structure xs 3; 21.2 ft between structure and xs
END DESCRIPTION:
XS GIS Cut Line= 3
 2261254.7010814417957.6236648492261457.32662871418468.232404687
2261782.53870622418942.404879296
#Sta/Elev= 30
       0 2362.42    51.2 2359.64   105.5 2354.33   163.1 2352.24   412.7 2348.66
   438.3 2347.06   512.2 2347.29   554.4 2344.65   628.1 2346.69   655.6 2344.96
   734.8 2345.28   816.8 2342.84   828.3 2340.91   839.8 2340.52852.28742340.819
   865.6  2343.1   879.7 2349.63   900.9 2352.58   923.2 2352.23   936.3 2346.02
   943.3 2345.09   963.5 2344.89   977.9  2346.5  1016.1  2345.8  1050.1 2347.36
  1054.9 2349.22  1069.5 2359.87  1113.1 2385.78    1118 2388.59  1124.3 2390.01
#Mann= 5 ,-1,0
       0      .1       0   828.3    .045       0852.2874     .07       0
  919.34     .06       0  969.34      .1       0
#XS Ineff= 3 ,-1
       0     806  2341.8     873  912.96  2342.7  912.96 1064.45 2354.63
Permanent Ineff=
       F       F       F
Bank Sta=828.3,852.2874
XS Rating Curve= 0 ,0
Exp/Cntr(USF)=0,0
Exp/Cntr=0.5,0.3

Type RM Length L Ch R = 1 ,1539    ,296,294.7,293
BEGIN DESCRIPTION:
structure xs 2; 28.4 ft between structure and xs
END DESCRIPTION:
XS GIS Cut Line= 3
2261207.88024163418003.5881227972261410.50578894418514.196862635
2261712.33622242418956.330918292
#Sta/Elev= 30
       0 2359.33    66.2 2353.18    83.5 2353.83   182.5 2350.71   389.6 2348.46
   436.4 2346.41   535.3 2346.67   569.6 2345.79   587.8 2343.39   611.1 2345.42
     645 2343.48     688 2344.77   722.6 2343.25   786.4 2343.36   819.3 2341.26
     829 2340.44840.65772341.222   848.4 2343.69   853.2 2342.91   867.8 2344.81
   886.6  2348.5   899.9 2352.61   906.5 2352.96   926.9 2352.46   941.3 2346.96
   974.3 2345.03  1022.7 2346.29  1030.5 2349.47  1048.9 2363.14  1084.7 2386.88
#Mann= 5 ,-1,0
       0      .1       0   819.3    .045       0840.6577     .07       0
  919.34     .06       0  999.34      .1       0
#XS Ineff= 3 ,-1
       0     813  2341.7     850  906.98  2342.7  906.98 1024.58  2353.9
Permanent Ineff=
       F       F       F
Bank Sta=819.3,840.6577
XS Rating Curve= 0 ,0
Exp/Cntr(USF)=0,0
Exp/Cntr=0.5,0.3

Type RM Length L Ch R = 1 ,1245    ,299.1,305.2,308.5
BEGIN DESCRIPTION:
structure xs 1
END DESCRIPTION:
XS GIS Cut Line= 3
2261073.81846055418219.6908858882261169.49352879418580.357090913
2261410.50578894419057.655880632
#Sta/Elev= 30
       0 2368.29    42.9 2354.53    63.6 2349.88      76 2348.66     340  2346.7
   361.6 2345.71   374.1 2343.61   429.3 2343.23   450.1 2341.98   463.7 2339.99
     477 2341.88     495 2338.63   521.9 2339.77   548.8 2339.43   566.3 2341.29
   583.2 2341.17     605 2342.61617.68032340.229   651.9 2339.53665.37922340.207
   674.3 2341.13   687.7 2340.42   715.2 2343.79   741.5 2342.88   759.4 2344.92
   852.2 2343.07   858.1  2344.1   878.9 2354.17   889.4 2354.56   907.8 2353.39
#Mann= 4 ,-1,0
       0      .1       0617.6803    .045       0665.3792      .1       0
  813.14     .07       0
#XS Ineff= 2 , 0
                          757.18         2347.15
Permanent Ineff=
       F       F
Bank Sta=617.6803,665.3792
XS Rating Curve= 0 ,0
Exp/Cntr(USF)=0,0
Exp/Cntr=0.3,0.1

Type RM Length L Ch R = 1 ,939     ,130.9,130.8,131.2
XS GIS Cut Line= 4
2260959.29405474418584.2157947912260955.70041386418682.374977191
2261122.28739642419244.3746818652261161.00228533419265.285299998
#Sta/Elev= 30
       0  2345.3      89 2344.97   113.7 2345.38   117.8 2345.09   134.5 2338.62
   142.9 2337.01     147 2337.45   155.4 2339.56   167.9    2340   201.3 2340.39
   213.8 2339.25   222.1 2339.06   238.8 2340.79   251.3 2341.23   272.2 2338.48
   280.5 2338.17   305.6 2339.69   343.1  2338.8  346.72 2339.75   351.5  2341.9
   355.6 2342.69   372.3 2342.64   397.4 2341.25   430.7 2341.48   501.7 2340.85
   554.6  2342.3   622.7 2340.88     664 2343.56   695.6  2343.5   728.4 2344.82
#Mann= 6 ,-1,0
       0      .1       0  138.22     .08       0  238.22      .1       0
   305.6    .045       0  346.72      .1       0  508.22     .05       0
#XS Ineff= 2 , 0
                          506.59         2348.18
Permanent Ineff=
       F       F
Bank Sta=305.6,346.72
XS Rating Curve= 0 ,0
Exp/Cntr(USF)=0,0
Exp/Cntr=0.3,0.1

Type RM Length L Ch R = 1 ,809     ,296.7,310.3,301.5
XS GIS Cut Line= 4
2260797.00680692418603.9718236832260904.37210892418968.204812561
2261027.35400385419257.3201444892261174.38643512419327.370744975
#Sta/Elev= 30
       0 2379.39    34.6 2365.84    55.5 2353.64    71.2 2347.06    80.5 2345.08
   106.6 2343.67   109.8    2343     118 2337.25   126.4 2336.72   145.2  2337.6
   154.9 2339.64   216.1 2340.79   234.8 2339.76   247.3 2337.79   259.8 2340.52
     280 2342.29     289 2341.96   299.8 2338.17   309.9 2338.82   319.2    2338
   357.8 2338.15   372.4 2340.61   409.9    2342   472.1 2340.53   563.5 2340.19
   645.9 2343.13   801.2 2343.26   836.6 2345.65   849.9 2349.04   856.8 2352.31
#Mann= 10 ,-1,0
       0      .1       0     120     .08       0     220      .1       0
     280     .08       0   319.2    .045       0   357.8      .1       0
  539.73     .05       0  639.73     .06       0  743.91     .05       0
  853.91     .07       0
#XS Ineff= 2 , 0
                          660.28         2348.94
Permanent Ineff=
       F       F
Bank Sta=319.2,357.8
XS Rating Curve= 0 ,0
Exp/Cntr(USF)=0,0
Exp/Cntr=0.3,0.1

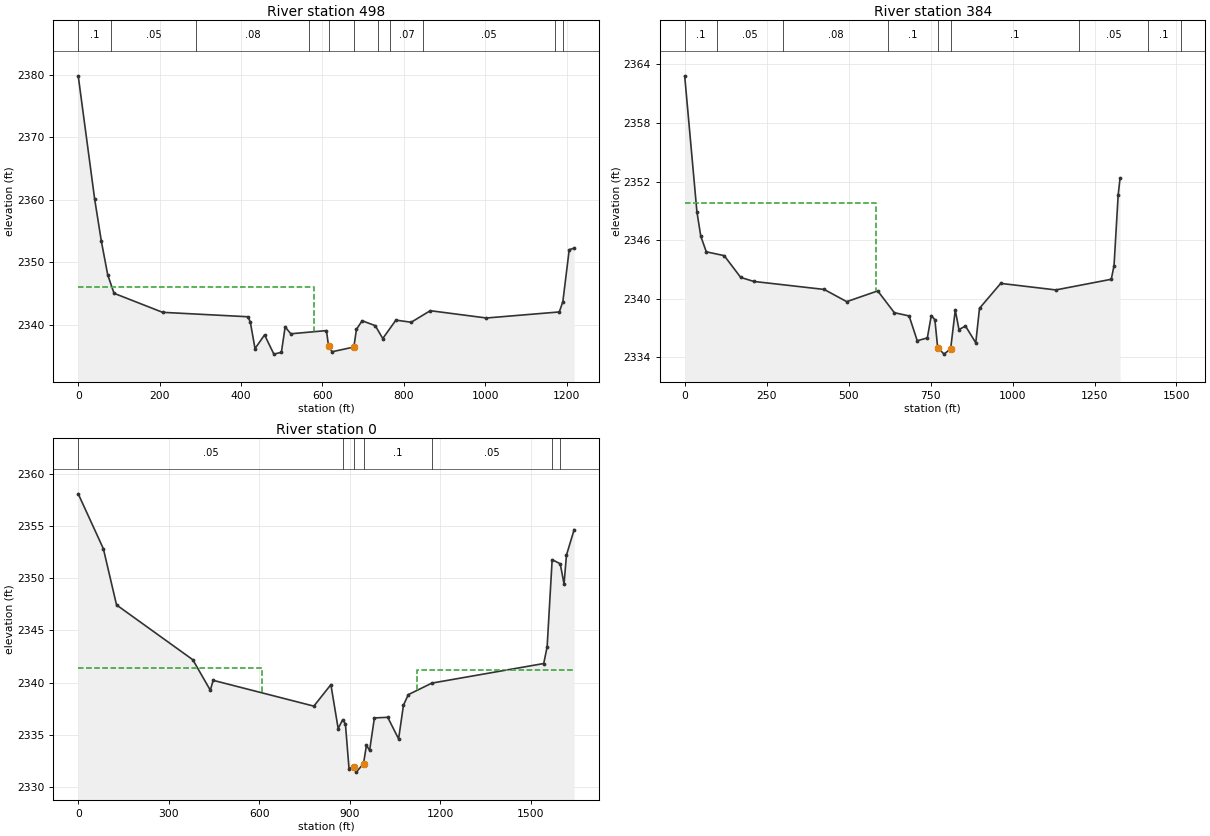
Type RM Length L Ch R = 1 ,498     ,129.2,114.5,112.3
XS GIS Cut Line= 4
2260725.67276057418542.1768968282260593.57436341418916.382825735
2260890.42662982419432.7298489722261097.61541228419523.686717874
#Sta/Elev= 30
       0 2379.87    40.5 2360.08    56.8 2353.38    72.5 2347.98      88 2345.02
   207.3 2341.97   416.9 2341.26   422.8 2340.44   434.5 2336.16   457.9 2338.35
   480.8 2335.27   499.3 2335.56   508.5 2339.63   522.4 2338.53     610 2339.04
615.09812336.611   623.8 2335.65677.29752336.407   683.8 2339.25   697.7 2340.62
     730 2339.83   748.4 2337.77   780.7 2340.72   818.3 2340.38   865.1 2342.23
  1003.1 2341.06  1182.2 2342.03  1190.9 2343.67  1206.6 2352.01  1218.7 2352.25
#Mann= 11 ,-1,0
       0      .1       0      80     .05       0     290     .08       0
  566.84      .1       0615.0981    .045       0677.2975      .1       0
  736.84     .08       0  766.84     .07       0  846.84     .05       0
 1172.43     .06       0 1192.43     .07       0
#XS Ineff= 2 , 0
          579.38 2346.05
Permanent Ineff=
       F       F
Bank Sta=615.0981,677.2975
XS Rating Curve= 0 ,0
Exp/Cntr(USF)=0,0
Exp/Cntr=0.3,0.1

Type RM Length L Ch R = 1 ,384     ,524.7,383.7,294
XS GIS Cut Line= 4
2260680.31600997418530.3766858572260503.71094741 419083.12380896
2260867.03084642419449.8642916432261085.50443256419525.966460299
#Sta/Elev= 30
       0 2362.82    37.3 2348.91    49.1 2346.41    65.9 2344.81   120.5 2344.42
   170.9 2342.19   210.7 2341.78   425.6 2340.96   494.2 2339.71   588.8 2340.81
   639.5 2338.58   684.5 2338.25   709.3 2335.71   740.1    2336   752.1 2338.29
   763.1 2337.86   771.6 2335.01   791.2 2334.34   811.2 2334.89   825.3 2338.84
   836.6 2336.85   856.4 2337.22   887.8  2335.5   899.2 2339.03   963.9 2341.58
    1132 2340.91  1301.1    2342  1309.5 2343.39  1322.2 2350.65  1327.9 2352.34
#Mann= 9 ,-1,0
       0      .1       0     100     .05       0     300     .08       0
     620      .1       0   771.6    .045       0   811.2      .1       0
  1202.6     .05       0  1412.6      .1       0  1512.6     .06       0
#XS Ineff= 2 , 0
          583.66 2349.83    1280         2341.69
Permanent Ineff=
       F       F
Bank Sta=771.6,811.2
XS Rating Curve= 0 ,0
Exp/Cntr(USF)=0,0
Exp/Cntr=0.3,0.1

Type RM Length L Ch R = 1 ,0       ,354.1,535.2,487.4
XS GIS Cut Line= 5
2259535.68015735419622.1317599862259981.22439533419474.109773259
2260117.70530399419486.1875013462260642.18520583419518.501936932
2261153.65234368419530.952461428
#Sta/Elev= 30
       0 2358.08    83.4 2352.82     127 2347.44   379.9 2342.19   437.8 2339.27
   447.3 2340.22     781 2337.75   837.4 2339.81   861.5  2335.6   876.52336.451
   885.5 2336.06   897.5 2331.77   913.4 2331.95   921.6 2331.43   945.6 2332.25
   955.2    2334   965.7 2333.51   981.6 2336.62  1025.8 2336.68  1061.8 2334.61
  1077.9 2337.84  1093.9 2338.85 1171.982339.954  1542.8 2341.83  1554.1 2343.44
  1570.7 2351.78  1597.5 2351.38  1610.1 2349.44  1618.1 2352.21  1643.6 2354.65
#Mann= 7 ,-1,0
       0     .05       0   876.5      .1       0   913.4    .045       0
   945.6      .1       0 1171.98     .05       0  1570.7     .06       0
  1597.5      .1       0
#XS Ineff= 2 , 0
          610.48 2341.38 1122.34         2341.18
Permanent Ineff=
       F       F
Bank Sta=913.4,945.6
XS Rating Curve= 0 ,0
Exp/Cntr=0.3,0.1
LCMann Table=0

Chan Stop Cuts=-1
Use User Specified Reach Order=0
Composite Channel Slope=5